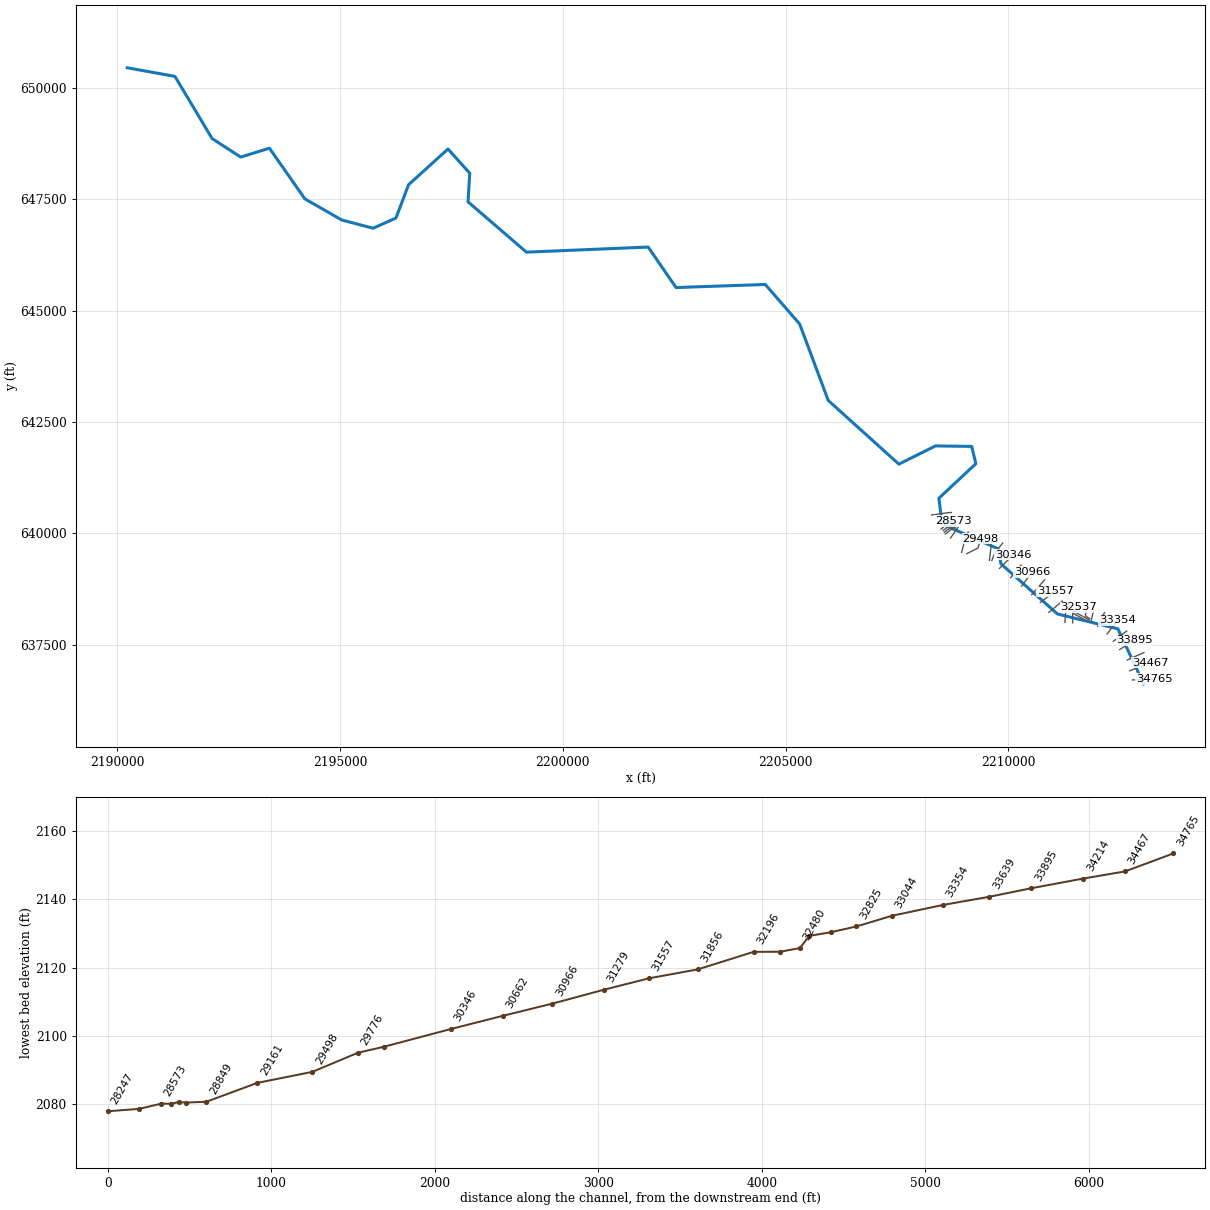
--- LFBUCKRV.prj (project) ---

Proj Title=LFBUCKRV
Current Plan=p01
Default Exp/Contr=0,0
English Units
Geom File=g01
Flow File=f01
Plan File=p01
BEGIN DESCRIPTION:
---------- MODELED AS PART OF WVEMD CTP PROGRAM, 2023----------
Stream Name: Left Fork Buckhannon River
Flood Zone:  AFH
Upshur County, WV
HEC-RAS Version: RAS 6.3
Vertical Datum: NAVD88
Projection: NAD 1983 StatePlane West Virginia S FIPS 4702 (US Feet)
Terrain: 1-meter LIDAR (FEMA Region III 3DEP collected 2016-2018)
Land Use: 2019 NLCD
Hydrologic Method:
WV 2010 Regional Regression Equations
Additional Model Notes:
Imported 3 shared XS's and snippet of streamline from Randolph model at upstream end
END DESCRIPTION:
DSS Export Rating Curves= 0
DSS Export Rating Curve Sorted= 0
DSS Export Volume Flow Curves= 0
DXF OffsetX= 0
DXF OffsetY= 0
DXF ScaleX= 0
DXF ScaleY= 0

--- LFBUCKRV.p01 (plan) ---

Plan Title=Floodplain
Program Version=6.31
Short Identifier=Floodplain
Geom File=g01
Flow File=f01
Subcritical Flow
K Sum by GR= 0
Std Step Tol= 0.01
Critical Tol= 0.01
Num of Std Step Trials= 20
Max Error Tol= 0.3
Flow Tol Ratio= 0.001
Split Flow NTrial= 30
Split Flow Tol= 0.02
Split Flow Ratio= 0.02
Log Output Level= 0
Friction Slope Method= 1
Unsteady Friction Slope Method= 2
Unsteady Bridges Friction Slope Method= 1
Parabolic Critical Depth
Global Vel Dist= 0 , 0 , 0
Global Log Level= 0
CheckData=True
Encroach Param=-1 ,0,0, 0
Mapping Interval=1HOUR
Computation Time Step Use Courant=        0
Computation Time Step Use Time Series=    0
Computation Time Step Count To Double=0
Computation Time Step Max Doubling=0
Computation Time Step Max Halving=0
Computation Time Step Residence Courant=0
Run HTab= 0
Run UNet= 0
Run Sediment= 0
Run PostProcess= 0
Run WQNet= 0
Run RASMapper=-1
UNET Theta= 0
UNET Theta Warmup= 0
UNET ZTol= 0
UNET ZSATol= 0
UNET MxIter= 0
UNET Max Iter WO Improvement= 0
UNET MaxInSteps= 0
UNET DtIC= 0
UNET DtMin= 0
UNET MaxCRTS= 0
UNET WFStab= 0
UNET SFStab= 0
UNET WFX= 1
UNET SFX= 1
UNET Gravity=32.17405
UNET 1D Methodology=Finite Difference
UNET DSS MLevel= 1
UNET Pardiso=0
UNET DZMax Abort= 0
UNET Use Existing IB Tables= 0
UNET Froude Reduction=False
UNET Froude Limit= 0
UNET Froude Power= 0
UNET D1 Cores= 0
UNET WindReference=Eulerian
UNET WindDragFormulation=Hsu (1988)
UNET D2 Coriolis=0
UNET D2 Cores= 0
UNET D2 Theta= 1
UNET D2 Theta Warmup= 1
UNET D2 Z Tol= 0.01
UNET D2 Volume Tol= 0.01
UNET D2 Max Iterations= 20
UNET D2 Equation= 0
UNET D2 RampUpFraction=0.1
UNET D2 TimeSlices= 1
UNET D2 Turbulence Formulation=Non-Conservative (original)
UNET D2 Eddy Viscosity=0.3
UNET D2 Transverse Eddy Viscosity=0.1
UNET D2 Smagorinsky Mixing=0
UNET D2 BCVolumeCheck=0
UNET D2 Cores=0
UNET D2 SolverType=PARDISO (Direct)
UNET D2 Minimum Iterations= 3
UNET D2 Maximum Iterations= 30
UNET D2 Restart Number= 10
UNET D2 Relaxation Coeff=1.3
UNET D2 SOR Precondition Iterations= 10
UNET D2 ILUT Maximum Fill= 8
UNET D2 ILUT Tolerance=1E-08
UNET D2 Convergence Tolerance=0.00001
UNET D1D2 MaxIter= 0
UNET D1D2 ZTol=0.01
UNET D1D2 QTol=0.1
UNET D1D2 MinQTol=1
Write IC File= 0
Write IC File at Fixed DateTime=0
Write IC File at Sim End=0
Echo Input=False
Echo Parameters=False
Echo Output=False
Write Detailed= 0
HDF Write Warmup=0
HDF Write Time Slices=0
HDF Flush=0
HDF Compression= 1
HDF Chunk Size= 1
HDF Spatial Parts= 1
HDF Use Max Rows=0
HDF Fixed Rows= 1
Calibration Method= 0
Calibration Iterations= 20
Calibration Max Change=0.05
Calibration Tolerance=0.2
Calibration Maximum=1.5
Calibration Minimum=0.5
Calibration Optimization Method= 1
WQ AD Non Conservative
WQ ULTIMATE=-1
WQ Max Comp Step=1HOUR
WQ Output Interval=15MIN
WQ Output Selected Increments= 0
WQ Create Restart=0
WQ Fixed Restart=0
WQ System Summary=0
WQ Write To DSS=0
Sorting and Armoring Iterations= 10
XS Update Threshold= 0.02
Bed Roughness Predictor= 0
Hydraulics Update Threshold= 0.02
Energy Slope Method= 1
Volume Change Method= 1
Sediment Retention Method= 0
Sediment TS Multiplier= 1
Warm Up Method= 0
XS Weighting Method= 0
Number of US Weighted Cross Sections= 1
Number of DS Weighted Cross Sections= 1
Upstream XS Weight=0
Main XS Weight=1
Downstream XS Weight=0
Number of DS XS's Weighted with US Boundary= 1
Upstream Boundary Weight= 1
Weight of XSs Associated with US Boundary= 0
Number of US XS's Weighted with DS Boundary= 1
Downstream Boundary Weight= 0.5
Weight of XSs Associated with DS Boundary= 0.5
Percentile Method= 0
Sediment Output Level= 3
Mass or Volume Output= 0
Output Increment Type= 1
Profile and TS Output Increment= 1
Transport Output Increment 1
XS Output Flag= 0
XS Output Increment= 10
Read HDF5 Sediment Hotstart= 0
Sediment Hotstart Type= 0
Write Gradation File= 0
Read Gradation Hotstart= 0
Write HDF5 File= 1
Write Binary Output= 1
Write DSS Sediment File= 0
DSS Sediment Output Type= 1
SV Curve= 0
Specific Gage Flag= 0
Subcell Erosion Methods= 0
Subcell Deposition Methods= 0
Advection Scheme= 1
Matrix Solver= 0
Implicit Weighting Factor= 1
Maximum Outer Loop Convergence Iterations= 5
Convergence Maximum Absolute= 0.001
Convergence RMSE= 0.0001
Grain Fractions Max Abs Error= 0.001
Max Subgrid Regions= 1
Max Subgrid Length Scale= 3.402823E+38
Initial Layer Thickness= 3.402823E+38
Min Layer Thickness= 3.402823E+38
Max Layer Thickness= 3.402823E+38
Number of Layers= 5

--- LFBUCKRV.f01 (steady flow) ---

Flow Title=Flows
Program Version=6.31
Number of Profiles= 1
Profile Names=01pct
River Rch & RM=LFBUCKRV,Main,34765
    4710
River Rch & RM=LFBUCKRV,Main,20421
    5350
Boundary for River Rch & Prof#=LFBUCKRV,Main            , 1
Up Type= 0
Dn Type= 3
Dn Slope=0.00442
DSS Import GetInterval= 0
DSS Import GetPeak= 0
DSS Import FillOption= 0

--- LFBUCKRV.g01 (geometry) ---

Geom Title=Geometry
Program Version=6.31

River Reach=LFBUCKRV        ,Main
Reach XY= 30
2213036.24817476636616.130237758     2212455.677637854.243000001
2211099.37500001 638187.738000022209831.66900001639313.736000001
2209770.37199999639650.1210000072208509.47700001640207.797999993
2208439.36700001640787.3940000092209269.09900004641562.555000007
2209175.03700002641950.7360000012208363.56199999 641962.21100001
2207540.81200004641552.5680000042205955.83700003642982.613999993
     2205314.572644699.2539999932204542.32999998      645588.022
2202539.49800003645518.9130000032201914.05800001646428.171000004
      2199182.08646313.9050000012197871.39200002647443.594000012
     2197910.654648085.8889999992197421.94300003648630.716999993
     2196536.609647827.3970000152196253.87900001647080.394999996
2195741.21699999646851.0639999962195039.71500002647035.553000018
2194209.52500005647510.4710000162193414.47499998 648649.26000002
2192770.09200002648448.7740000192192128.05400003648864.999000013
2191294.23000003650260.7919999962190223.54794142650454.868443087

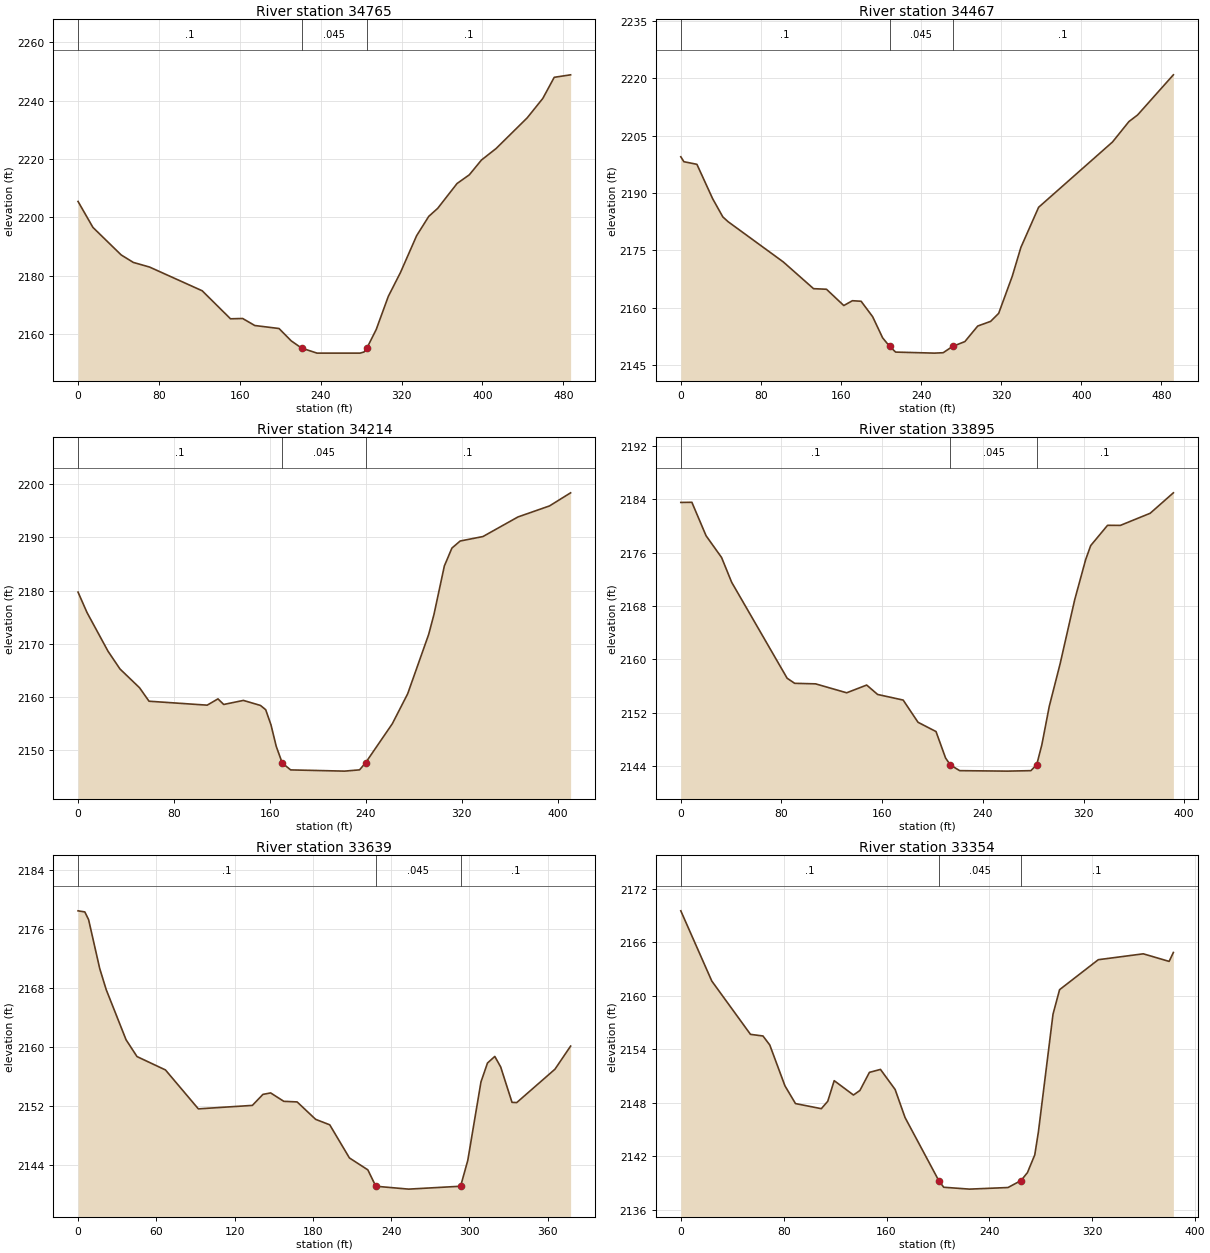
Type RM Length L Ch R = 1 ,34765   ,289.3,297.4,311.4
XS GIS Cut Line= 2
2212781.51854692636706.0752715142213268.32829419636725.659571691
#Sta/Elev= 30
       0 2205.45    14.7 2196.56    42.7  2187.1    54.7 2184.54    70.7 2182.96
   122.8 2174.82   150.8 2165.21   162.8 2165.32   174.8 2162.91   198.8 2161.88
   210.8 2157.66   221.1 2155.17   236.4 2153.44   278.9 2153.44   282.9 2153.83
  285.752155.204   294.9 2161.52   306.9 2172.91   318.9 2181.08   334.9 2193.71
   346.9 2200.34   355.7 2203.07   374.9 2211.61     387 2214.58     399 2219.65
   413.5  2223.6   444.3 2234.13   459.7 2240.78     471 2248.02   487.2 2248.87
#Mann= 3 ,-1,0
       0      .1       0   221.1    .045       0  285.75      .1       0
Bank Sta=221.1,285.75
XS Rating Curve= 0 ,0
Exp/Cntr(USF)=0,0
Exp/Cntr=0.3,0.1

Type RM Length L Ch R = 1 ,34467   ,252.5,253.6,255.2
XS GIS Cut Line= 2
 2212721.2749462636910.6239836612213177.30936461637095.275956762
#Sta/Elev= 30
       0 2199.51     3.1 2198.22    16.1 2197.54    31.8 2188.55      42 2183.78
    47.2 2182.54   102.4    2172   132.6 2165.01   145.5 2164.86   162.8  2160.6
   171.4 2161.86   180.1 2161.72   191.6 2157.69   201.6 2152.15  208.592149.914
   214.6 2148.42   253.4 2148.15   262.1 2148.26   271.4  2149.9   283.7 2151.16
   296.6 2155.24   309.5 2156.46   317.5 2158.55   331.1 2168.28   339.7 2175.81
   357.4  2186.3   431.2 2203.38   447.6 2208.72   456.3 2210.46     492 2220.95
#Mann= 3 ,-1,0
       0      .1       0  208.59    .045       0   271.4      .1       0
Bank Sta=208.59,271.4
XS Rating Curve= 0 ,0
Exp/Cntr(USF)=0,0
Exp/Cntr=0.3,0.1

Type RM Length L Ch R = 1 ,34214   ,314.4,318.2,324.2
XS GIS Cut Line= 2
2212665.31980283   637153.7712662213040.21926337637321.636696092
#Sta/Elev= 30
       0 2179.71     7.5 2175.87      25 2168.61      35 2165.27    51.3 2161.75
    59.2 2159.22   107.7 2158.48   116.7 2159.66   121.5 2158.61   137.9 2159.37
   152.1 2158.43   156.5 2157.63   160.9 2154.79   165.3 2150.74  170.31 2147.61
   177.3 2146.32   222.3 2146.09   234.8 2146.33   239.82147.656   262.1 2154.99
   274.9 2160.61   292.4 2171.75   296.8 2175.48   305.5 2184.62   311.8 2187.98
   318.7 2189.31   337.7 2190.15   366.9 2193.83   393.2  2195.9   410.8 2198.36
#Mann= 3 ,-1,0
       0      .1       0  170.31    .045       0   239.8      .1       0
Bank Sta=170.31,239.8
XS Rating Curve= 0 ,0
Exp/Cntr(USF)=0,0
Exp/Cntr=0.3,0.1

Type RM Length L Ch R = 1 ,33895   ,253.8,256.4,259.8
XS GIS Cut Line= 2
2212496.75087049637388.8779414462212827.72636404637597.772310326
#Sta/Elev= 30
       0 2183.51     8.8 2183.53    20.1 2178.51    32.4 2175.26    40.4 2171.55
    84.5 2157.16    90.5  2156.4   107.1 2156.32   131.8 2154.98   147.7 2156.14
   156.4 2154.73   176.7 2153.89   188.5 2150.56   202.8 2149.17   210.4  2145.2
   214.22144.166   221.6 2143.31   259.5 2143.24   278.2 2143.31  282.832144.214
   286.9  2147.2   292.8 2152.96   301.4 2159.32     313 2168.93   321.7 2174.94
   325.7 2177.04   339.1 2180.08   349.3 2180.07     373 2181.89   391.4 2184.95
#Mann= 3 ,-1,0
       0      .1       0   214.2    .045       0  282.83      .1       0
Bank Sta=214.2,282.83
XS Rating Curve= 0 ,0
Exp/Cntr(USF)=0,0
Exp/Cntr=0.3,0.1

Type RM Length L Ch R = 1 ,33639   ,275.8,284.5,293.3
XS GIS Cut Line= 2
2212354.99026604637575.0303100992212654.77117812637804.517766929
#Sta/Elev= 30
       0 2178.44     5.2 2178.29     8.1 2177.24    16.6 2170.63    21.6 2167.76
    36.8 2160.98    45.2  2158.7      67 2156.89    92.2 2151.62   133.6 2152.09
   141.7 2153.58   147.6 2153.78   157.7 2152.64   167.9 2152.56   182.1  2150.2
   192.9 2149.46     208 2144.97   222.1 2143.36   228.2 2141.14   253.4 2140.75
  293.192141.142   298.7 2144.65   308.8 2155.27   313.8 2157.83   319.4 2158.72
   323.9  2157.3   332.6  2152.5   336.2 2152.47   365.5 2156.99   377.5 2160.12
#Mann= 3 ,-1,0
       0      .1       0   228.2    .045       0  293.19      .1       0
Bank Sta=228.2,293.19
XS Rating Curve= 0 ,0
Exp/Cntr(USF)=0,0
Exp/Cntr=0.3,0.1

Type RM Length L Ch R = 1 ,33354   ,304.6,311,317.2
XS GIS Cut Line= 2
2212213.94732641637737.9067303912212444.54500634638043.863129255
#Sta/Elev= 30
       0 2169.54    24.1 2161.67    54.2 2155.69    63.9 2155.51    69.2  2154.5
      81 2149.92    89.2 2147.93   109.3 2147.36   114.3 2148.19   119.3  2150.5
   134.3 2148.89   139.3  2149.4   146.7 2151.43   155.3 2151.76   166.7 2149.51
   174.4 2146.37  200.742139.271   204.5 2138.55   224.5 2138.34   254.5 2138.52
   264.6  2139.3   269.6 2140.19   275.3 2142.18   278.1 2144.73   289.5 2157.96
   294.6  2160.7   324.7 2164.06   359.7 2164.72   379.8 2163.87   383.1 2164.87
#Mann= 3 ,-1,0
       0      .1       0  200.74    .045       0   264.6      .1       0
Bank Sta=200.74,264.6
XS Rating Curve= 0 ,0
Exp/Cntr(USF)=0,0
Exp/Cntr=0.3,0.1

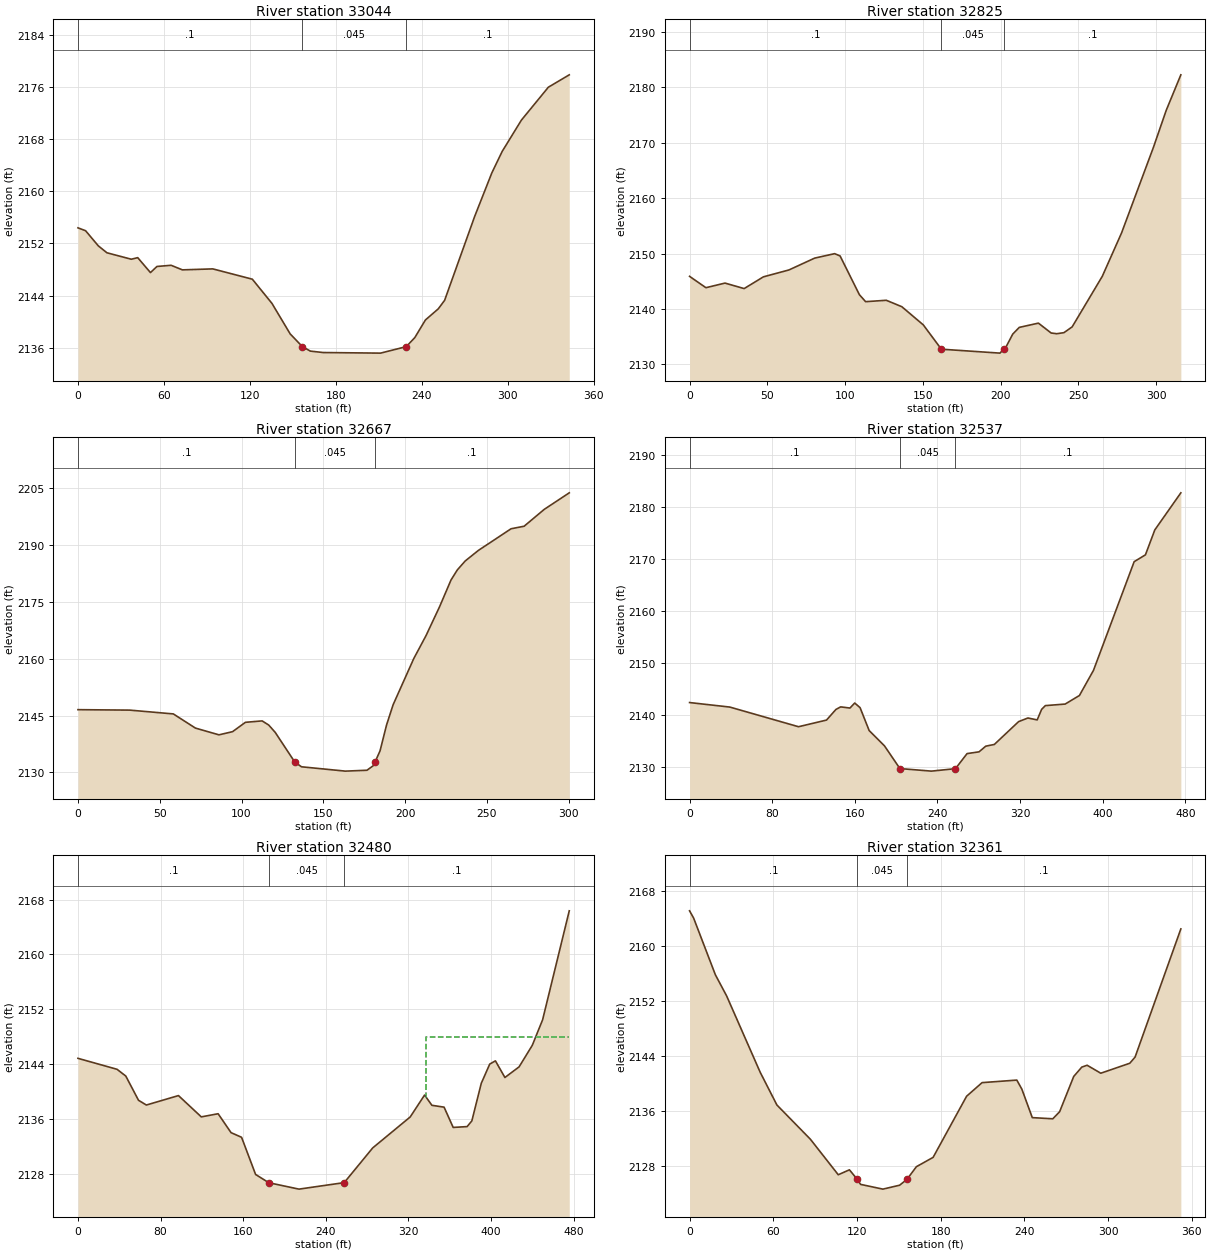
Type RM Length L Ch R = 1 ,33044   ,213.8,218.7,224.6
XS GIS Cut Line= 2
2212002.41752579637911.8417173852212154.65055716638219.126910339
#Sta/Elev= 30
       0 2154.39     5.3 2153.95    14.2 2151.63    20.2 2150.57    37.2 2149.58
    41.7 2149.82    50.6 2147.53    55.1 2148.47      65 2148.65    72.9 2147.95
    94.1  2148.1   121.7 2146.52   135.4 2142.81   148.1 2138.14  156.562136.198
   162.2  2135.5   171.1 2135.28   211.2 2135.19   229.2 2136.19   229.2  2136.2
   235.1 2137.57   242.5 2140.27   251.5 2141.98   255.9 2143.28   276.9 2156.15
   288.9 2162.83   296.1 2166.11   309.5  2170.9   328.3 2175.94   342.9 2177.84
#Mann= 3 ,-1,0
       0      .1       0  156.56    .045       0   229.2      .1       0
Bank Sta=156.56,229.2
XS Rating Curve= 0 ,0
Exp/Cntr(USF)=0,0
Exp/Cntr=0.3,0.1

Type RM Length L Ch R = 1 ,32825   ,153.1,157.4,160.7
XS GIS Cut Line= 2
 2211845.9557991637995.0060585972211919.25318458638302.291251552
#Sta/Elev= 30
       0 2145.89    10.5 2143.84    22.8 2144.67    35.1 2143.68    47.5  2145.8
    63.9 2147.04    80.4 2149.17    93.3 2149.98    96.8 2149.56   109.2 2142.58
   113.2 2141.32   126.5 2141.57   136.5 2140.41   150.3 2137.13   161.9 2132.75
   199.6 2132.04  202.032132.769   203.7 2133.27   207.8 2135.47     212 2136.68
   224.3 2137.45   232.5 2135.67   236.1 2135.54   240.7 2135.73     246 2136.77
   265.4  2145.9   277.8 2153.73   298.3 2169.18   306.5 2175.83   315.9 2182.23
#Mann= 3 ,-1,0
       0      .1       0   161.9    .045       0  202.03      .1       0
Bank Sta=161.9,202.03
XS Rating Curve= 0 ,0
Exp/Cntr(USF)=0,0
Exp/Cntr=0.3,0.1

Type RM Length L Ch R = 1 ,32667   ,102.9,130.6,156.8
XS GIS Cut Line= 3
2211822.38765986638085.0667734482211730.33808019638139.518637481
2211740.70986381638332.693107501
#Sta/Elev= 30
       0 2146.54    31.6 2146.42    58.3 2145.42    71.8 2141.69    86.2 2139.91
    94.5 2140.74   102.4 2143.21   112.6 2143.58   116.6  2142.5   120.6 2140.56
   132.6 2132.72   136.7 2131.49   163.5 2130.35   176.7 2130.58   180.7 2131.83
  181.612132.708   184.7 2135.69   188.7 2142.53   192.7 2147.84   205.3 2159.98
   212.8 2166.03   221.1 2173.65   228.1  2180.7   231.9 2183.32   236.8 2185.72
   244.8 2188.48   264.8 2194.19   272.8 2194.86   285.1  2199.3   300.4 2203.66
#Mann= 3 ,-1,0
       0      .1       0   132.6    .045       0  181.61      .1       0
Bank Sta=132.6,181.61
XS Rating Curve= 0 ,0
Exp/Cntr(USF)=0,0
Exp/Cntr=0.3,0.1

Type RM Length L Ch R = 1 ,32537   ,49.1,56.9,58.4
XS GIS Cut Line= 3
2211809.18729333638058.8198900442211512.33288215 638217.39596439
2211579.56913768638339.182389488
#Sta/Elev= 30
       0 2142.48      39 2141.61   105.5 2137.83   132.6 2139.11   141.7 2141.15
   146.3 2141.65   155.3 2141.42   159.9 2142.39   165.1  2141.5   173.9 2137.09
   188.7 2134.16  203.662129.782   234.2 2129.29  257.452129.762   268.7 2132.66
   280.3    2133   286.8 2134.09   295.1 2134.42   318.6 2138.81   327.6 2139.51
   336.6 2139.14   340.9 2141.17   344.5 2141.89   363.7 2142.19   377.5 2143.84
   391.1 2148.67   430.5 2169.58   441.4 2170.89   450.5 2175.69   475.7 2182.82
#Mann= 3 ,-1,0
       0      .1       0  203.66    .045       0  257.45      .1       0
Bank Sta=203.66,257.45
XS Rating Curve= 0 ,0
Exp/Cntr(USF)=0,0
Exp/Cntr=0.3,0.1

Type RM Length L Ch R = 1 ,32480   ,155.3,119.4,89.7
XS GIS Cut Line= 3
2211755.90573235638035.3506310412211459.05132117638193.926705387
 2211526.2875767638315.713130485
#Sta/Elev= 30
       0 2144.83    37.8 2143.23    46.3 2142.24    58.6 2138.71    66.2 2138.01
    97.3 2139.39   119.4 2136.28   135.7 2136.74   148.2 2133.98   158.4  2133.3
     172 2127.87  184.772126.665     214 2125.73   257.8 2126.68   285.4 2131.75
   321.7 2136.27   335.6 2139.47   342.7 2137.97   354.5  2137.7   363.3 2134.74
   376.8 2134.86   381.4  2135.7   390.5 2141.18   398.7 2143.99   404.2 2144.46
   413.4 2142.03   427.1 2143.58   439.9 2146.73   449.9 2150.46   475.7 2166.37
#Mann= 3 ,-1,0
       0      .1       0  184.77    .045       0   257.8      .1       0
#XS Ineff= 2 , 0
                          337.46         2147.95
Permanent Ineff=
       F       F
Bank Sta=184.77,257.8
XS Rating Curve= 0 ,0
Exp/Cntr(USF)=0,0
Exp/Cntr=0.3,0.1

Type RM Length L Ch R = 1 ,32361   ,166.4,164.2,162.5
XS GIS Cut Line= 3
2211439.92813868637986.5348290082211441.22461163638216.010541717
2211512.53062405638315.838959111
#Sta/Elev= 30
       0 2165.13     2.9 2164.08    18.5 2155.83    26.6 2152.74    50.6 2141.66
    62.6 2136.89    86.6 2131.91   106.6 2126.74   114.6 2127.46  119.982126.137
   122.6 2125.34   138.6 2124.65   150.6 2125.22   155.92126.082   162.6 2127.91
   174.6 2129.27   198.6 2138.16   209.7 2140.14   234.6 2140.51   238.2  2139.2
   245.7 2135.05   260.4 2134.88   265.3 2135.91   275.4 2141.04   281.2  2142.4
     285 2142.67   294.8 2141.51   315.6 2142.96   319.4 2143.86   352.2  2162.5
#Mann= 3 ,-1,0
       0      .1       0  119.98    .045       0   155.9      .1       0
Bank Sta=119.98,155.9
XS Rating Curve= 0 ,0
Exp/Cntr(USF)=0,0
Exp/Cntr=0.3,0.1

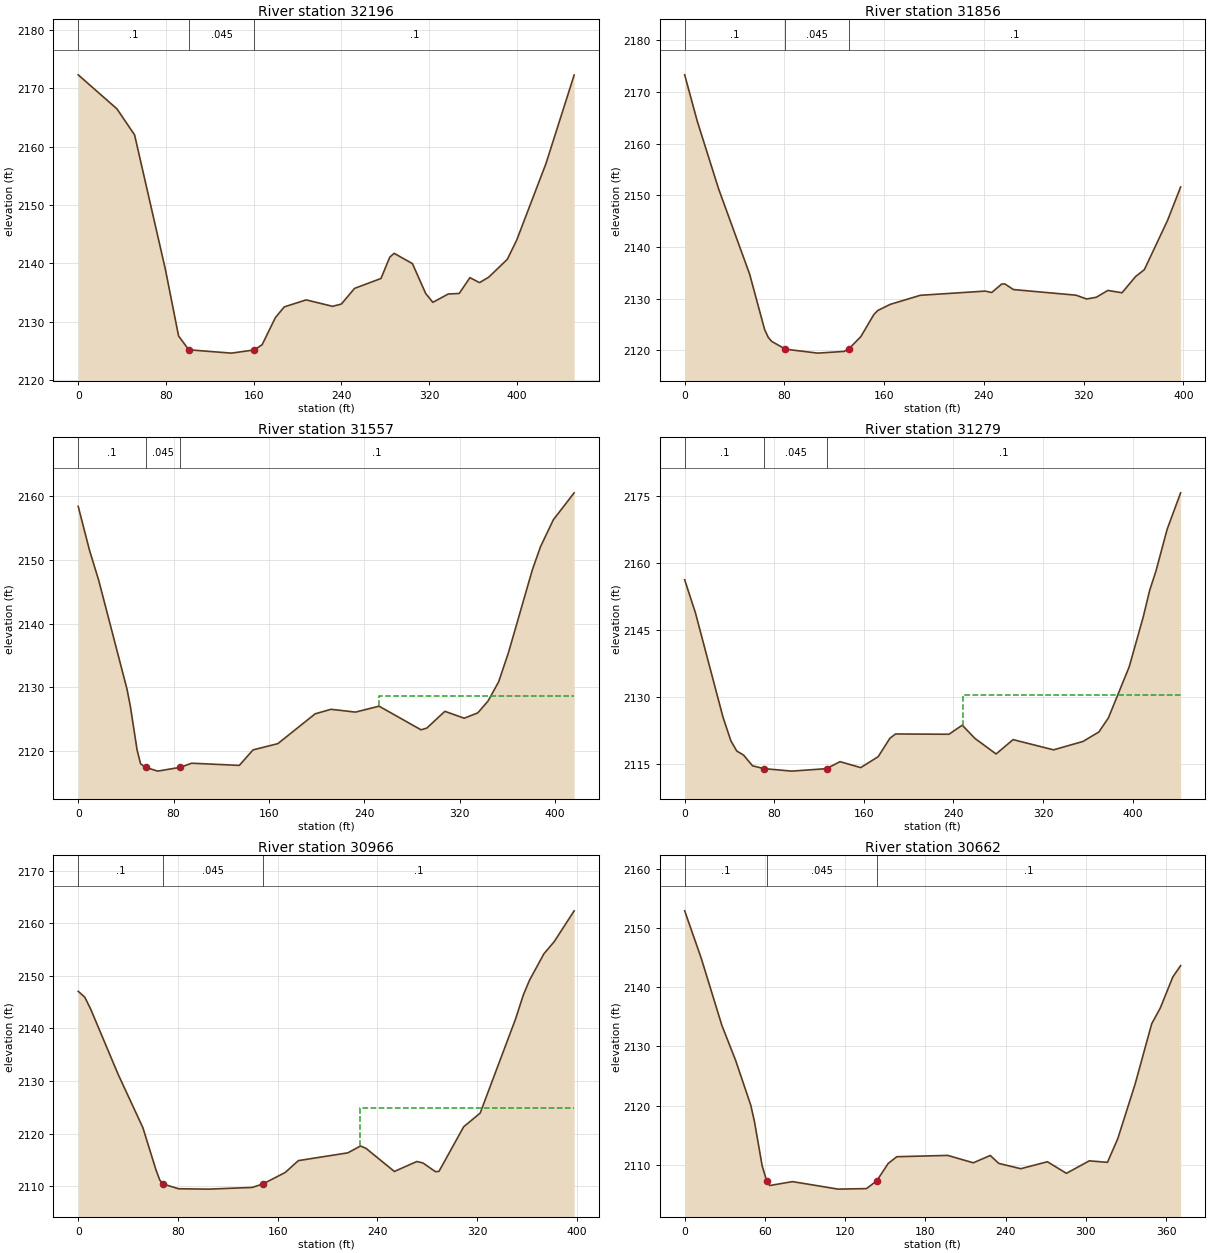
Type RM Length L Ch R = 1 ,32196   ,361.6,340,317.6
XS GIS Cut Line= 3
2211267.49142336637997.9266774952211289.05776948638290.975262887
2211393.08367425638410.224470795
#Sta/Elev= 30
       0 2172.29    35.3 2166.46    51.4    2162    79.5 2138.93    91.5 2127.55
   100.8 2125.18   139.6 2124.61   160.6 2125.16   167.7 2126.06   179.7 2130.68
   187.8 2132.53   207.8 2133.73   231.9 2132.63   239.9 2133.02   251.9  2135.7
     276  2137.4     284 2141.04     288 2141.71   304.7 2139.94   316.8 2134.82
   323.3 2133.31   337.3 2134.74   347.3 2134.83   357.1 2137.54   365.8 2136.69
   374.2 2137.62   391.2 2140.69   399.7 2143.96   426.4 2157.08   452.1 2172.25
#Mann= 3 ,-1,0
       0      .1       0   100.8    .045       0   160.6      .1       0
Bank Sta=100.8,160.6
XS Rating Curve= 0 ,0
Exp/Cntr(USF)=0,0
Exp/Cntr=0.3,0.1

Type RM Length L Ch R = 1 ,31856   ,297.9,299.1,299.7
XS GIS Cut Line= 2
2210908.47519105638222.4703987692211211.67264519638479.997943507
#Sta/Elev= 30
       0 2173.29    10.1 2164.33    27.2 2151.26    52.1 2134.77    64.1 2124.07
      67 2122.56    69.8 2121.76   80.832120.255   106.7 2119.49   127.8 2119.82
  131.622120.302   141.3 2122.68   151.8 2126.98   154.9 2127.73   164.8 2128.91
     189 2130.67     241 2131.48   246.3 2131.21   254.3 2132.85   256.8 2132.87
   263.7 2131.78   313.9 2130.69   322.4 2129.96   330.2 2130.29   339.4 2131.61
   350.8 2131.16   361.7  2134.3   368.7 2135.62   387.3 2145.14   397.8  2151.6
#Mann= 3 ,-1,0
       0      .1       0   80.83    .045       0  131.62      .1       0
Bank Sta=80.83,131.62
XS Rating Curve= 0 ,0
Exp/Cntr(USF)=0,0
Exp/Cntr=0.3,0.1

Type RM Length L Ch R = 1 ,31557   ,272.4,278.3,283.1
XS GIS Cut Line= 2
2210714.37807605638445.7455114492211046.75352787638695.661404618
#Sta/Elev= 30
       0  2158.4     9.4 2151.57    17.3 2146.73    40.9 2129.75    43.7 2127.08
    49.4 2120.17    52.3 2118.03   56.522117.472    66.6 2116.87    85.6 2117.47
    95.1 2118.11   135.1 2117.77   146.6  2120.2   167.4 2121.18   198.7 2125.86
     212 2126.57   232.5 2126.13   252.3 2127.06   287.5 2123.35   292.3 2123.62
   307.5 2126.25   323.7 2125.17   335.1 2126.01   343.7 2127.87   352.6 2130.89
   360.8 2135.45   380.8 2148.42   387.6 2152.04   398.4 2156.29   415.9 2160.53
#Mann= 3 ,-1,0
       0      .1       0   56.52    .045       0    85.6      .1       0
#XS Ineff= 2 , 0
                          252.35          2128.6
Permanent Ineff=
       F       F
Bank Sta=56.52,85.6
XS Rating Curve= 0 ,0
Exp/Cntr(USF)=0,0
Exp/Cntr=0.3,0.1

Type RM Length L Ch R = 1 ,31279   ,309.2,312.7,313.5
XS GIS Cut Line= 2
2210521.94150222638617.9177983472210810.04191468638954.357206196
#Sta/Elev= 30
       0 2156.31     9.6 2148.93    34.2  2125.6    41.2 2120.32    46.5    2118
    52.6 2117.09    60.6 2114.69    71.1 2114.05    95.7  2113.5  126.752114.055
   138.7 2115.62   157.2 2114.29   172.8 2116.73   183.3 2120.86   188.3 2121.81
     236 2121.75   247.9 2123.78   259.2 2120.82   278.1 2117.34   293.3 2120.55
   329.4 2118.26   355.7 2120.14   369.9 2122.26   378.4  2125.4     397 2136.85
   409.6 2148.08   415.2 2153.89   420.9 2158.29   430.9 2167.63   442.9 2175.77
#Mann= 3 ,-1,0
       0      .1       0    71.1    .045       0  126.75      .1       0
#XS Ineff= 2 , 0
                          248.62         2130.48
Permanent Ineff=
       F       F
Bank Sta=71.1,126.75
XS Rating Curve= 0 ,0
Exp/Cntr(USF)=0,0
Exp/Cntr=0.3,0.1

Type RM Length L Ch R = 1 ,30966   ,305.6,304,303.1
XS GIS Cut Line= 2
2210292.71798612638813.1686684882210533.91023747639129.537725455
#Sta/Elev= 30
       0 2147.07     5.3 2145.95    10.1 2143.63    32.1 2131.25    51.9 2121.13
    62.4 2113.11    65.4 2111.19    68.1 2110.43    80.5 2109.53   104.7 2109.46
   139.5 2109.78   148.12110.438     166 2112.62   176.6 2114.88   216.3 2116.36
   226.4 2117.66   230.8 2117.22   253.6 2112.82   271.6 2114.71   276.5 2114.44
   286.7 2112.76   289.4 2112.85   309.2 2121.32   322.4 2123.91   350.7 2141.74
   357.1 2146.42     362 2149.18   373.5 2154.19   381.8 2156.51   397.8 2162.37
#Mann= 3 ,-1,0
       0      .1       0    68.1    .045       0   148.1      .1       0
#XS Ineff= 2 , 0
                          226.18         2124.95
Permanent Ineff=
       F       F
Bank Sta=68.1,148.1
XS Rating Curve= 0 ,0
Exp/Cntr(USF)=0,0
Exp/Cntr=0.3,0.1

Type RM Length L Ch R = 1 ,30662   ,320.2,316.5,314.5
XS GIS Cut Line= 2
2210048.39336787638999.5444990782210281.75470197639287.722253939
#Sta/Elev= 30
       0 2152.92    12.4  2144.9    27.8 2133.57    38.1 2127.64    49.4 2120.08
    52.2 2117.28    57.9 2109.86   61.272107.297    63.6 2106.49    80.6 2107.15
   114.8 2105.88   135.9 2105.97  143.532107.258   152.2 2110.23   158.6 2111.36
   196.7 2111.58   215.8 2110.33   228.5 2111.57   234.8 2110.23   251.3 2109.33
   271.2 2110.51   285.4 2108.55   302.5 2110.66   316.1 2110.41   323.8  2114.4
   336.7 2123.57   349.2 2133.84   355.6 2136.49     365 2141.76   370.8 2143.65
#Mann= 3 ,-1,0
       0      .1       0   61.27    .045       0  143.53      .1       0
Bank Sta=61.27,143.53
XS Rating Curve= 0 ,0
Exp/Cntr(USF)=0,0
Exp/Cntr=0.3,0.1

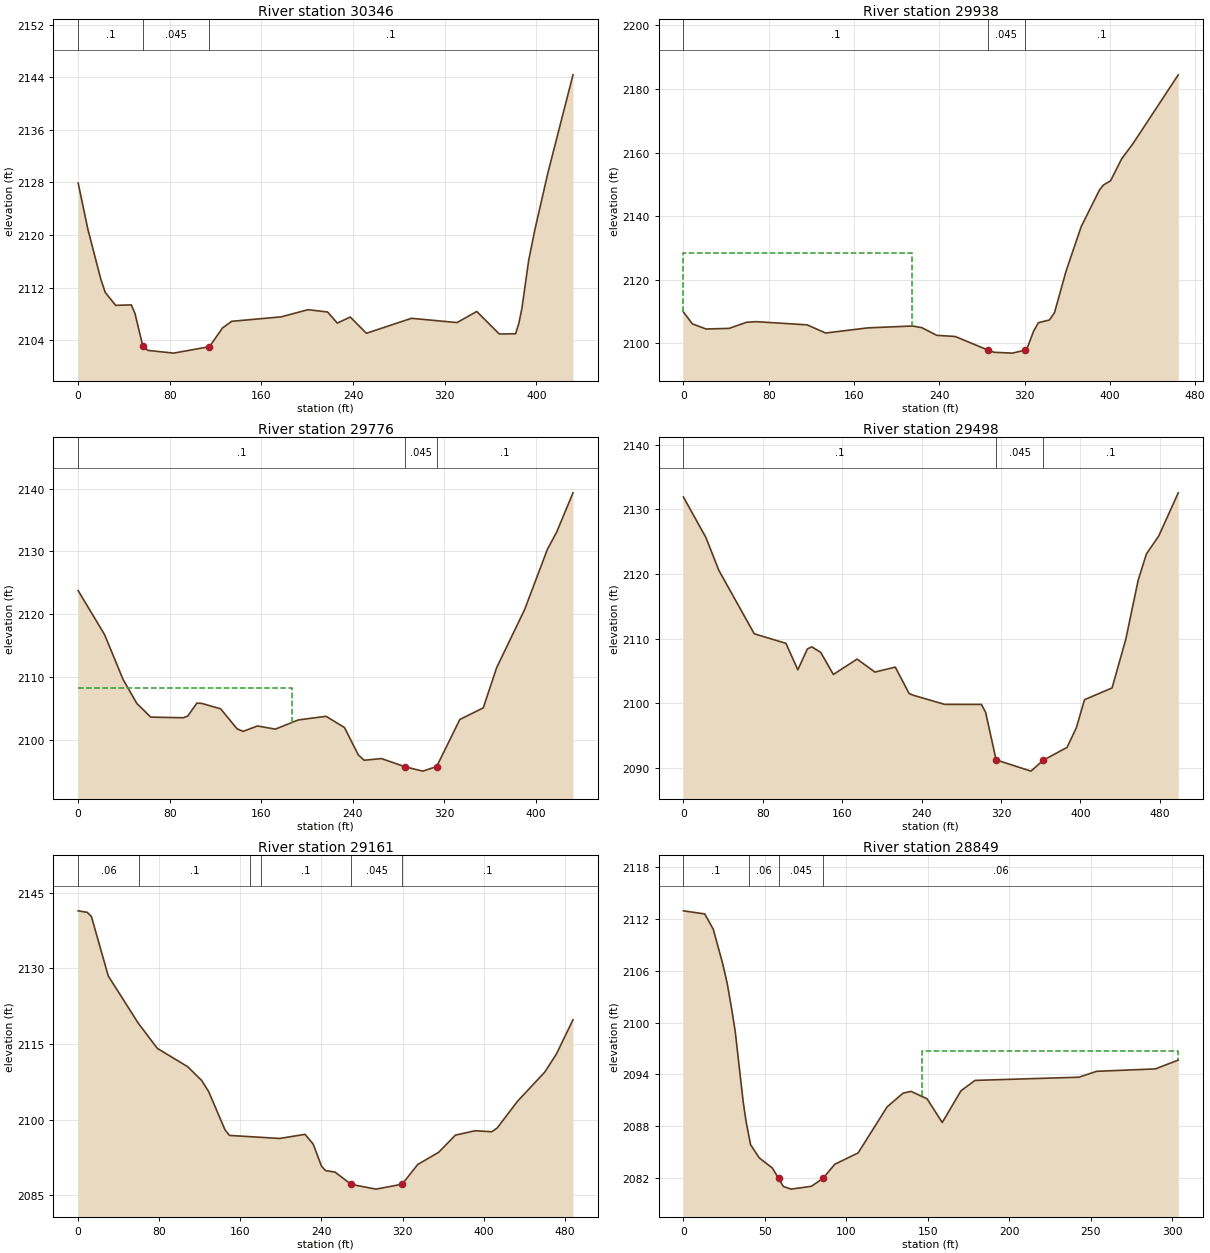
Type RM Length L Ch R = 1 ,30346   ,416.8,407.7,404.9
XS GIS Cut Line= 2
2209800.93638272639212.5454483232210107.90833898639516.385037687
#Sta/Elev= 30
       0 2127.92     8.4 2120.94    19.7 2113.33    23.6 2111.28    32.7  2109.3
    46.4 2109.37    49.6 2108.07    56.5 2103.04    60.8 2102.45    83.3 2102.03
   114.6 2103.01     126 2105.86     134 2106.87   177.2 2107.55   200.7 2108.64
   217.7 2108.29   226.2  2106.6   237.5 2107.52   251.6 2105.05   290.9 2107.33
   330.7 2106.68   347.9 2108.37   367.6 2104.94   381.8 2104.98   384.6 2106.53
   387.3 2108.83   393.2 2116.12   398.7 2120.87     410 2129.46   431.9 2144.38
#Mann= 3 ,-1,0
       0      .1       0    56.5    .045       0   114.6      .1       0
Bank Sta=56.5,114.6
XS Rating Curve= 0 ,0
Exp/Cntr(USF)=0,0
Exp/Cntr=0.3,0.1

Type RM Length L Ch R = 1 ,29938   ,153.6,161.8,172
XS GIS Cut Line= 3
2209626.87553733639389.3833879732209701.43569687639575.258715268
2209870.50873469639777.936332035
#Sta/Elev= 30
       0 2109.81     8.4 2106.07    21.3 2104.45    42.9 2104.65    59.3 2106.58
    68.5 2106.76   116.1 2105.76   133.4 2103.19   173.1 2104.81   214.9  2105.4
   223.6 2104.88   237.7 2102.46   254.9  2102.1   285.7 2097.83   291.6 2097.12
   308.7 2096.86     320 2097.76   322.9 2098.81   328.5 2103.76     333 2106.44
   343.4  2107.3   348.2 2109.69     359 2122.71   373.1 2136.64   390.3 2148.21
   393.9 2149.74   400.7 2151.11   411.1 2158.01   421.6 2162.73   464.2 2184.46
#Mann= 3 ,-1,0
       0      .1       0   285.7    .045       0     320      .1       0
#XS Ineff= 2 , 0
          214.08 2128.47
Permanent Ineff=
       F       F
Bank Sta=285.7,320
XS Rating Curve= 0 ,0
Exp/Cntr(USF)=0,0
Exp/Cntr=0.3,0.1

Type RM Length L Ch R = 1 ,29776   ,283.6,278.3,275.7
XS GIS Cut Line= 2
2209572.27359897639394.2227285612209625.52383628639823.356993952
#Sta/Elev= 30
       0 2123.78    23.1 2116.78    39.3 2109.63    51.3 2105.83    63.4 2103.66
    91.7 2103.56    95.7 2103.81   103.7 2105.88   107.8 2105.85   124.5 2104.98
   138.8 2101.81   144.1 2101.39   156.7 2102.25   172.3 2101.75   192.4 2103.21
   216.6 2103.79   232.7 2102.01   244.8 2097.65     250  2096.8     265 2097.07
   285.8 2095.75   301.2 2095.07   313.3  2095.8   333.5 2103.28     354 2105.13
   365.7 2111.53   390.1 2120.75   410.1 2130.37   418.1 2133.07   432.4 2139.33
#Mann= 3 ,-1,0
       0      .1       0   285.8    .045       0   313.3      .1       0
#XS Ineff= 2 , 0
          186.47 2108.35
Permanent Ineff=
       F       F
Bank Sta=285.8,313.3
XS Rating Curve= 0 ,0
Exp/Cntr(USF)=0,0
Exp/Cntr=0.3,0.1

Type RM Length L Ch R = 1 ,29498   ,337.7,336.6,339.3
XS GIS Cut Line= 3
2209064.13603921639542.8872286042209316.95039924639667.341096786
2209375.54975421639876.066418312
#Sta/Elev= 30
       0 2131.93    22.7 2125.65    35.7 2120.58    71.4 2110.75   103.3 2109.27
   115.3 2105.17   124.9  2108.4   129.3 2108.73   138.3 2107.88   151.1 2104.45
     175 2106.83     193 2104.82   213.5 2105.59   227.4  2101.5   231.9 2101.22
   263.1 2099.82   300.3 2099.81   304.5 2098.59   315.1 2091.22   350.2 2089.48
   362.6 2091.17   386.5 2093.15   395.9 2096.18   404.2 2100.55   431.9 2102.36
   445.7 2109.87   458.2 2119.03   466.5 2123.11     479 2125.91   498.6 2132.58
#Mann= 3 ,-1,0
       0      .1       0   315.1    .045       0   362.6      .1       0
Bank Sta=315.1,362.6
XS Rating Curve= 0 ,0
Exp/Cntr(USF)=0,0
Exp/Cntr=0.3,0.1

Type RM Length L Ch R = 1 ,29161   ,314.2,312,303.3
XS GIS Cut Line= 3
2208948.97125693639568.4364679132209051.44992714639972.550469295
2209097.85536271640026.690144121
#Sta/Elev= 30
       0 2141.39       9 2141.09    13.1 2140.25    29.7 2128.49    59.2 2119.16
    78.1 2114.14   108.1  2110.5   121.8 2107.79   128.7  2105.6   144.8 2098.03
   149.3 2096.89   198.8 2096.29   223.8 2097.11   231.9 2095.16   240.1 2090.79
   244.2 2089.91   253.4 2089.63  269.392087.185   293.8 2086.25  319.632087.224
     335 2091.13   355.7 2093.55   372.2 2096.95   391.7 2097.82   408.1 2097.62
   413.4 2098.36   433.5 2103.67   460.4 2109.45   471.8 2113.01   488.2  2119.8
#Mann= 6 ,-1,0
       0     .06       0      60      .1       0     170     .06       0
     180      .1       0  269.39    .045       0  319.63      .1       0
Bank Sta=269.39,319.63
XS Rating Curve= 0 ,0
Exp/Cntr(USF)=0,0
Exp/Cntr=0.3,0.1

Type RM Length L Ch R = 1 ,28849   ,127.8,123.8,117.5
XS GIS Cut Line= 2
2208700.60170309639895.2761244572208876.34675027640142.897089016
#Sta/Elev= 30
       0 2112.93    13.1 2112.57    18.3 2110.81      24 2106.89    26.9 2104.51
    29.7 2101.47    31.8 2098.96    36.7  2090.8    38.4 2088.61    41.2 2085.88
    46.5 2084.35    54.6 2083.17    58.4 2081.96    61.3 2081.04    66.1 2080.73
    78.5 2081.06   85.542081.962    92.9 2083.61   107.2 2084.92     125 2090.25
   134.8 2091.84   139.7 2092.04   149.5 2091.18   158.8 2088.44   170.3 2092.11
   178.9 2093.31   242.7 2093.68   253.5 2094.36   289.5 2094.64   303.6 2095.66
#Mann= 4 ,-1,0
       0      .1       0      40     .06       0    58.4    .045       0
   85.54     .06       0
#XS Ineff= 2 , 0
                          146.31         2096.76
Permanent Ineff=
       F       F
Bank Sta=58.4,85.54
XS Rating Curve= 0 ,0
Exp/Cntr(USF)=0,0
Exp/Cntr=0.3,0.1

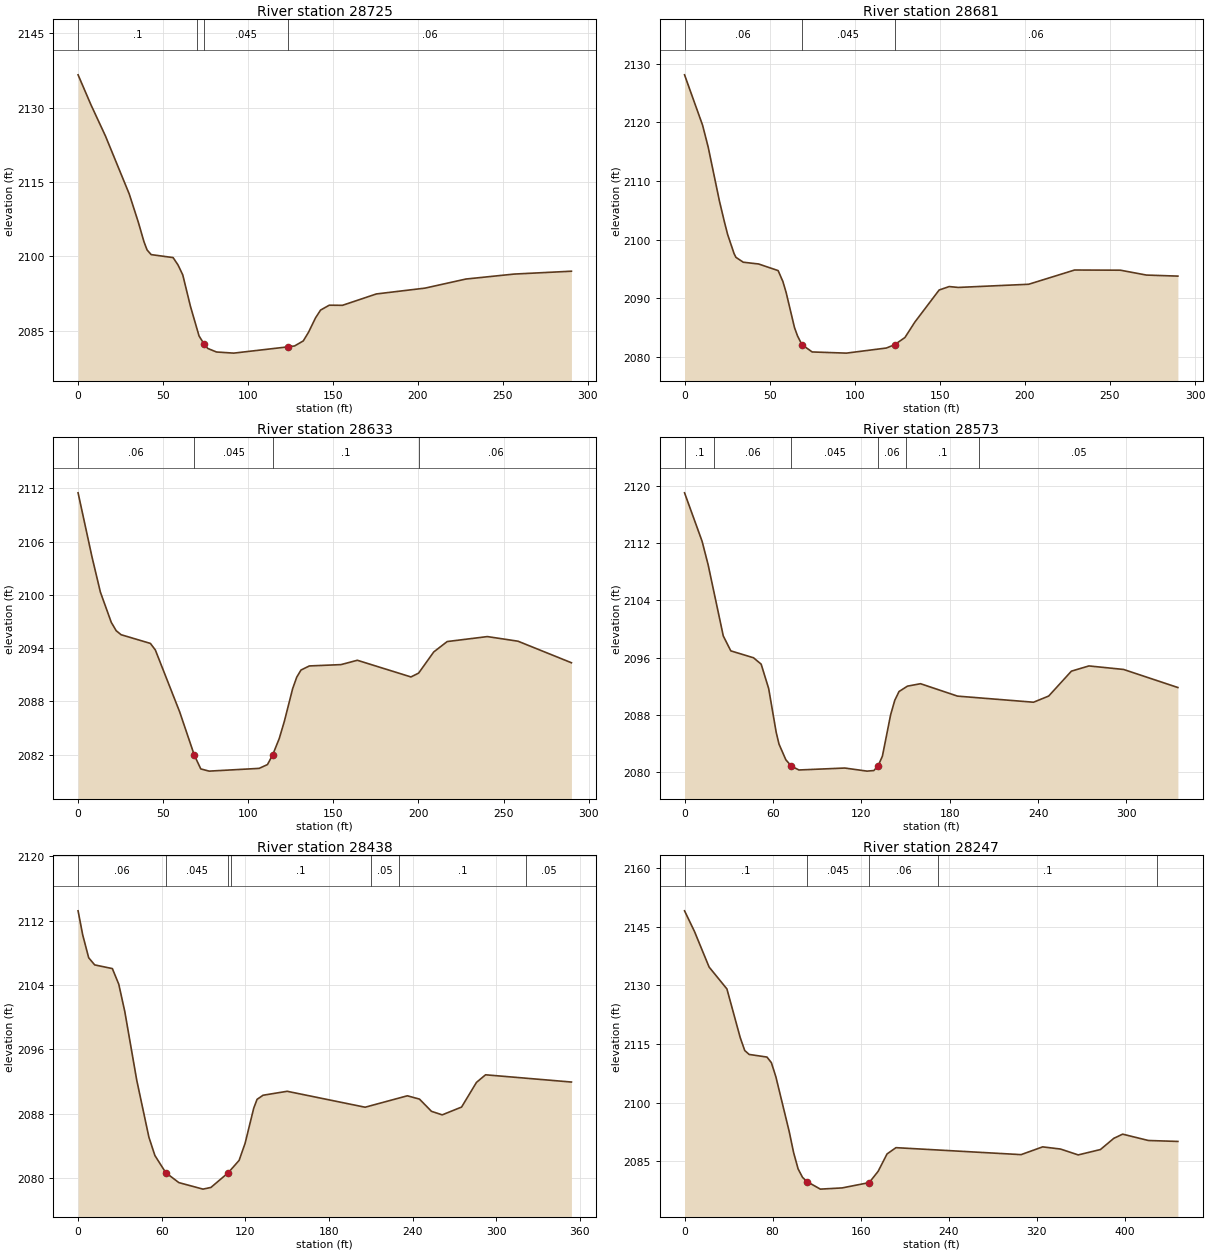
Type RM Length L Ch R = 1 ,28725   ,45.4,44.4,43.1
XS GIS Cut Line= 3
 2208584.3322747639982.4745046252208740.80359542640106.391389488
 2208822.7147566640145.246683894
#Sta/Elev= 30
       0 2136.63     7.5 2130.64    16.1 2124.29    30.1 2112.59    35.5 2106.83
    38.8 2102.92    40.6 2101.29      43 2100.35    55.9 2099.75    58.8 2098.27
    61.6 2096.26    66.1 2089.94    71.2 2083.92    74.32082.234    76.3 2081.42
    81.4  2080.7    91.6 2080.47   123.52081.735   127.4 2081.92   132.5 2082.93
   135.6 2084.68   139.7 2087.57   142.7 2089.16   147.8 2090.14   155.6 2090.12
   175.5 2092.41   204.2 2093.59   228.2 2095.42   256.5 2096.42   290.3    2097
#Mann= 4 ,-1,0
       0      .1       0      70     .06       0    74.3    .045       0
   123.5     .06       0
Bank Sta=74.3,123.5
XS Rating Curve= 0 ,0
Exp/Cntr(USF)=0,0
Exp/Cntr=0.3,0.1

Type RM Length L Ch R = 1 ,28681   ,47.3,48.2,47.9
XS GIS Cut Line= 3
2208559.56891943640025.1393576082208682.20108359640112.532394136
2208806.24281285640175.962823875
#Sta/Elev= 30
       0 2128.09    10.6  2119.5    13.9 2115.76    20.5 2106.57    23.4 2103.05
    25.3 2100.89    29.1 2097.61    30.2 2096.97    34.5 2096.14    43.5 2095.84
      55 2094.71    57.8 2092.84    59.7 2090.97    64.6    2085    66.4 2083.57
   68.972082.087      75 2080.84    95.1 2080.64   118.6 2081.51   123.5 2082.09
   129.5  2083.3   135.3 2085.92   149.6  2091.4   155.5 2091.99   160.8 2091.84
   202.2 2092.38   229.2 2094.81   256.1 2094.78   271.4 2093.95   289.9 2093.77
#Mann= 3 ,-1,0
       0     .06       0   68.97    .045       0   123.5     .06       0
Bank Sta=68.97,123.5
XS Rating Curve= 0 ,0
Exp/Cntr(USF)=0,0
Exp/Cntr=0.3,0.1

Type RM Length L Ch R = 1 ,28633   ,59,60,60.8
XS GIS Cut Line= 3
2208533.49196498640064.6071805562208656.12412914640152.000217085
2208780.16585841640215.430646823
#Sta/Elev= 30
       0 2111.51     8.2 2104.26    13.1 2100.32    19.5 2096.91    22.4 2095.96
    25.3 2095.51    42.5 2094.53    45.4 2093.79    59.7 2086.81    68.3 2081.93
    72.1 2080.38      77 2080.13   106.4 2080.44   111.3 2080.87  114.382081.977
   118.2  2083.8   121.2 2085.74   126.1 2089.44   128.5 2090.73     131 2091.53
   135.9 2091.99   154.5 2092.14   164.1 2092.63   195.6 2090.75   200.1 2091.18
     209 2093.57   216.9 2094.74   240.5  2095.3   258.5 2094.78   289.9 2092.35
#Mann= 4 ,-1,0
       0     .06       0    68.3    .045       0  114.38      .1       0
  200.59     .06       0
Bank Sta=68.3,114.38
XS Rating Curve= 0 ,0
Exp/Cntr(USF)=0,0
Exp/Cntr=0.3,0.1

Type RM Length L Ch R = 1 ,28573   ,141.6,134.9,128.5
XS GIS Cut Line= 3
2208487.71911023640096.9401016592208704.04858719640271.263854941
2208761.04077009640274.759505944
#Sta/Elev= 30
       0 2118.98    11.9 2112.23      16 2108.96    26.3 2099.02    31.4 2096.94
    46.8 2095.98      52 2095.09    57.1 2091.69    62.2  2085.6    64.1 2083.95
    68.8 2081.74    72.5 2080.88    77.6 2080.33   108.8  2080.6   123.9 2080.17
   128.5 2080.25   131.4 2080.92   134.3 2082.25   139.9 2088.03   142.7 2090.04
   145.6 2091.27   151.3 2092.02   160.2 2092.36   185.3 2090.63   236.9 2089.78
   247.2 2090.64   262.6 2094.11   274.5 2094.84     298 2094.35   334.9 2091.83
#Mann= 6 ,-1,0
       0      .1       0      20     .06       0    72.5    .045       0
   131.4     .06       0     150      .1       0     200     .05       0
Bank Sta=72.5,131.4
XS Rating Curve= 0 ,0
Exp/Cntr(USF)=0,0
Exp/Cntr=0.3,0.1

Type RM Length L Ch R = 1 ,28438   ,191.2,191.5,176
XS GIS Cut Line= 3
2208405.09909354640232.2595637082208693.97292994640348.853220566
2208736.14279842640353.010274036
#Sta/Elev= 30
       0 2113.22     3.3 2110.24     7.6 2107.39    11.9  2106.5    24.6 2106.04
    29.2 2104.09    33.5 2100.71    42.1 2092.15    50.8 2085.09    55.1 2082.81
   62.932080.669    72.3 2079.44    89.6 2078.63    95.3 2078.84   107.6 2080.65
   115.5  2082.2   119.8 2084.32     126 2088.69   128.4 2089.79   132.7  2090.3
     150 2090.79   205.9 2088.81   236.2 2090.23   244.9 2089.82   253.5  2088.3
   261.2 2087.86   275.1 2088.83   285.8  2091.9   292.3 2092.84   353.9 2091.94
#Mann= 7 ,-1,0
       0     .06       0   62.93    .045       0   107.6     .06       0
     110      .1       0     210     .05       0     230      .1       0
  321.52     .05       0
Bank Sta=62.93,107.6
XS Rating Curve= 0 ,0
Exp/Cntr(USF)=0,0
Exp/Cntr=0.3,0.1

Type RM Length L Ch R = 1 ,28247   ,239.7,235.2,225.7
XS GIS Cut Line= 3
2208274.06370902640409.1527622282208659.38946098640464.481588151
2208718.35853295640466.829573079
#Sta/Elev= 30
       0 2149.02       9 2143.77    22.3 2134.67    38.5 2129.07    50.6 2116.63
    54.7 2113.34    58.7 2112.34    74.9 2111.67    78.9 2110.24      83 2106.62
    95.1 2092.65    99.1 2087.28   103.2  2083.1   107.2 2080.95   111.4 2079.84
   123.4 2077.94   143.2 2078.25   167.8 2079.61   175.9 2082.48     184 2086.92
   192.1 2088.53   305.8 2086.75   325.4 2088.73   341.6 2088.18   357.7 2086.68
   377.9 2088.05   390.1 2090.92   398.1 2091.98   421.5 2090.36   448.3 2090.12
#Mann= 5 ,-1,0
       0      .1       0   111.4    .045       0   167.8     .06       0
     230      .1       0  429.28     .05       0
Bank Sta=111.4,167.8
XS Rating Curve= 0 ,0
Exp/Cntr(USF)=0,0
Exp/Cntr=0.3,0.1