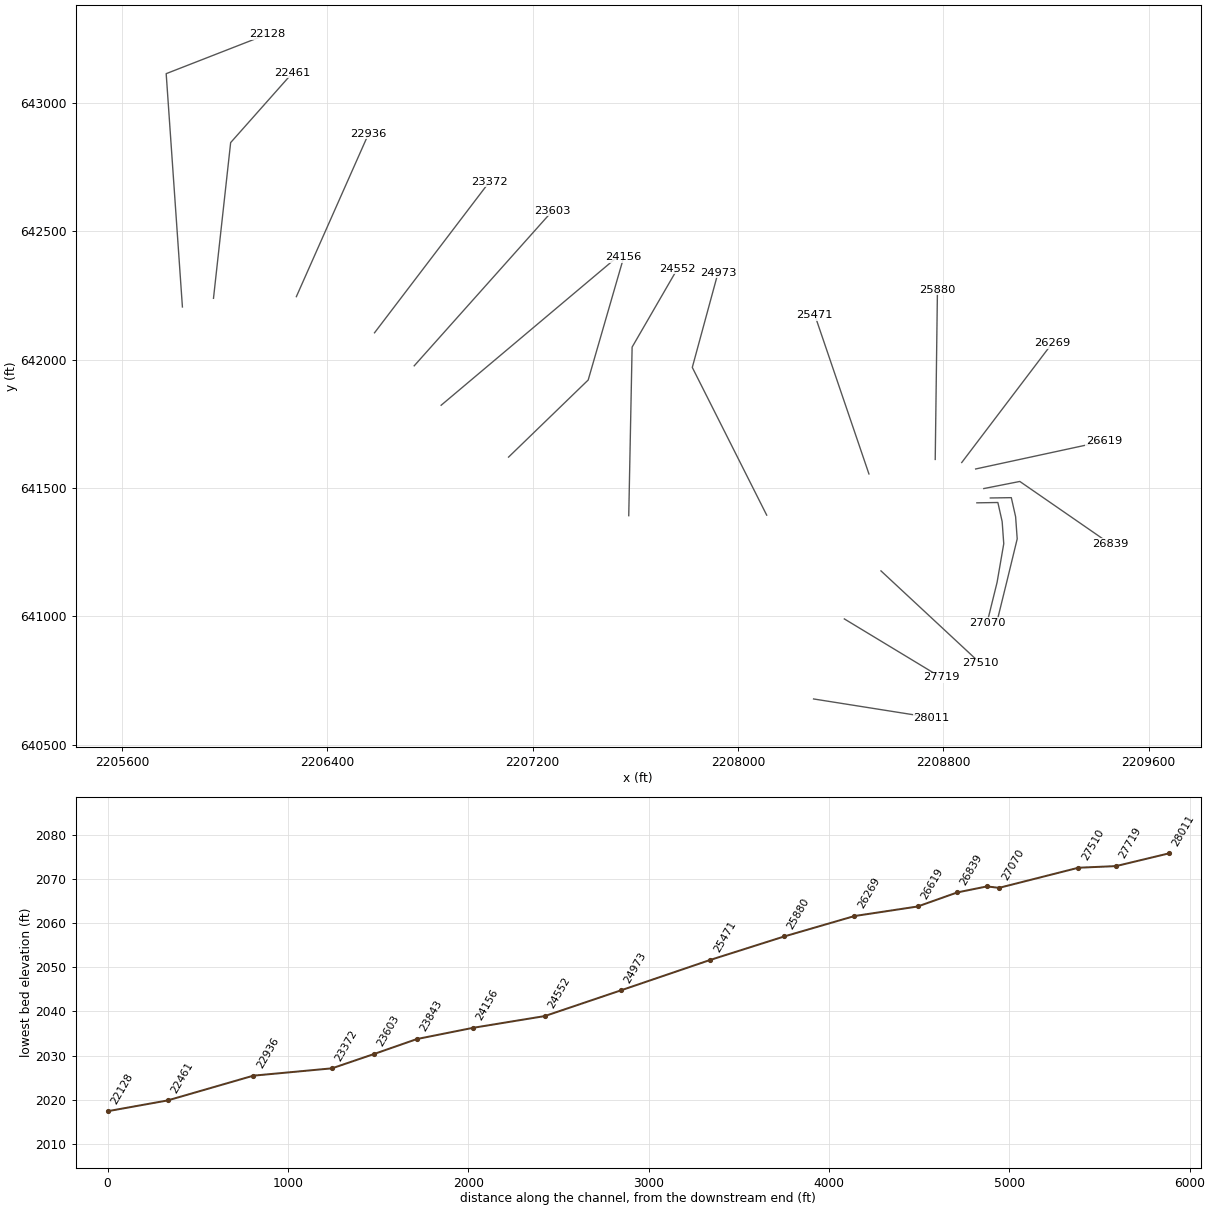
HEC-RAS study LFBUCKRV.prj: LFBUCKRV

--- LFBUCKRV.g01 (geometry) --- (continued)

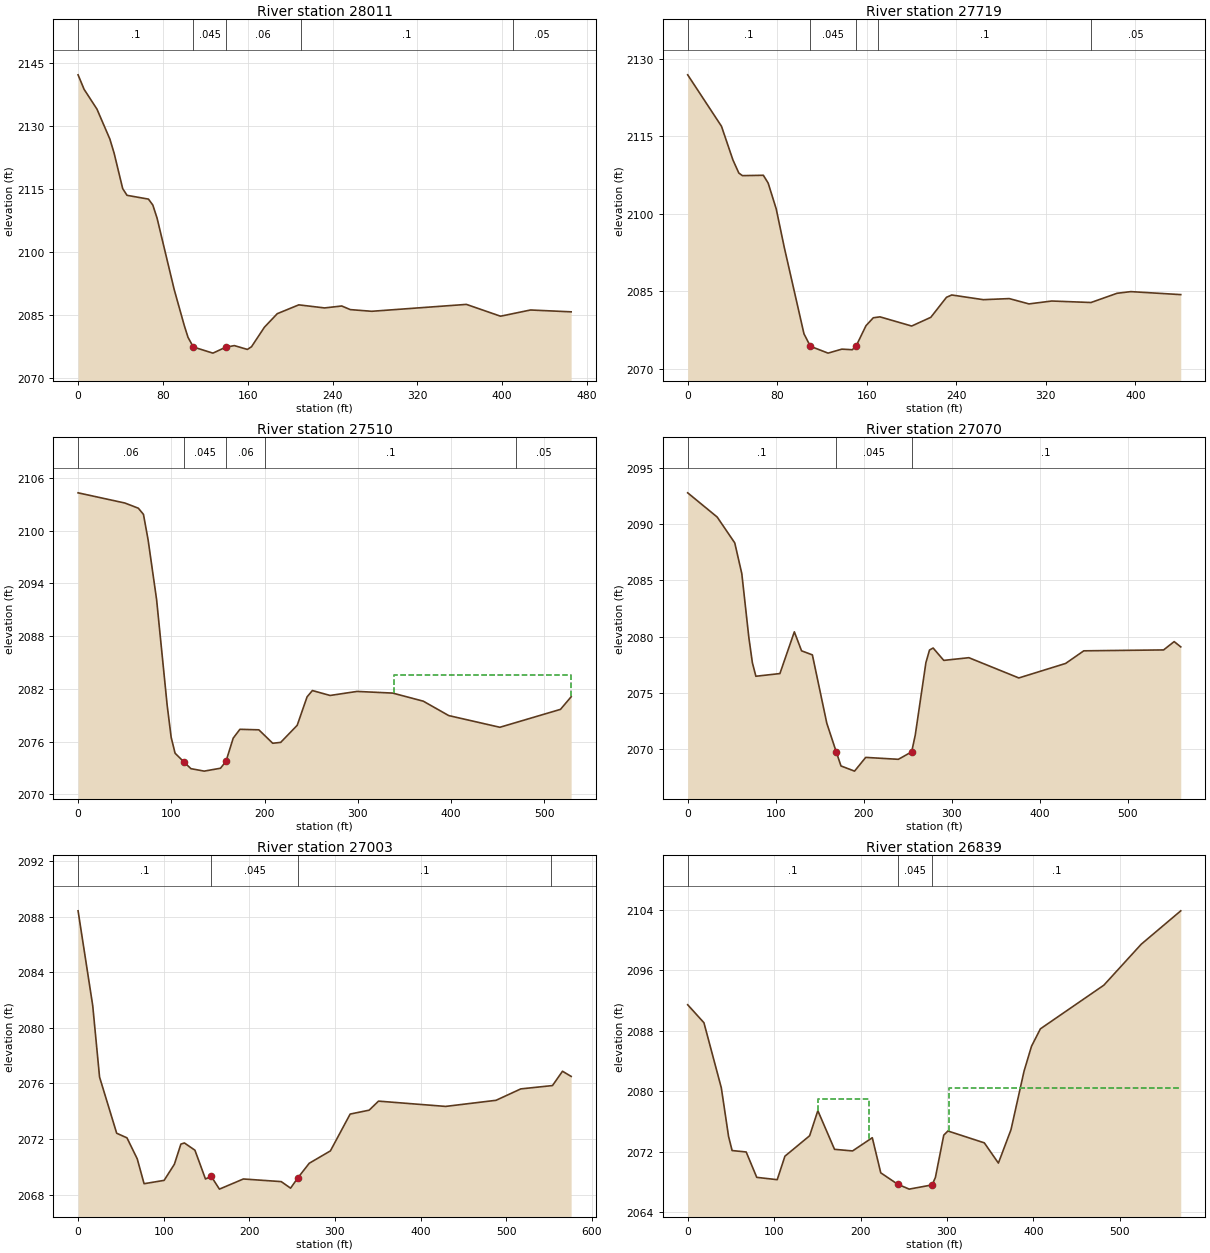
Type RM Length L Ch R = 1 ,28011   ,300.1,292.5,287
XS GIS Cut Line= 2
2208294.57585966640678.267361087 2208753.9270639640605.546843788
#Sta/Elev= 30
       0 2142.07     5.7 2138.62    17.8 2133.92      30 2126.79      34 2123.44
    42.1    2115    46.2 2113.41    66.4 2112.51    70.5 2111.11    74.5 2108.01
    90.7 2090.98   100.2 2082.43   103.7 2079.64108.70992077.337   127.2 2075.88
   139.3 2077.29   147.4 2077.67   159.7 2076.76   163.6  2077.4   175.8 2082.05
   187.9 2085.26   208.2 2087.36   232.5 2086.63   248.7 2087.09   256.8 2086.23
     277 2085.83   366.3 2087.47   398.5 2084.66   426.8 2086.14   465.1  2085.7
#Mann= 5 ,-1,0
       0      .1       0108.7099    .045       0   139.3     .06       0
     210      .1       0     410     .05       0
#XS Ineff= 2 , 0
                          576.46         2091.28
Permanent Ineff=
       F       F
Bank Sta=108.7099,139.3
XS Rating Curve= 0 ,0
Exp/Cntr(USF)=0,0
Exp/Cntr=0.3,0.1

Type RM Length L Ch R = 1 ,27719   ,214.1,208.4,205.6
XS GIS Cut Line= 2
2208414.36180332640990.105434425 2208791.2740214640762.048379973
#Sta/Elev= 30
       0 2126.94    30.2 2116.97    40.4 2110.45    45.7  2107.9    48.9  2107.4
    67.6 2107.47    71.9 2105.96    79.1 2100.95    86.3 2093.49   103.9 2076.74
   109.6 2074.33   125.4    2073   137.7 2073.77   147.1 2073.66   150.5 2074.39
   159.3 2078.32   165.8 2079.85   171.8 2080.03   200.1 2078.25   217.2 2079.94
   231.2 2083.82   235.9 2084.27   264.1 2083.36   287.3 2083.57   304.9 2082.54
   325.3  2083.1   360.3 2082.81   383.6  2084.6   395.9 2084.92   440.5 2084.34
#Mann= 5 ,-1,0
       0      .1       0   109.6    .045       0   150.5     .06       0
     170      .1       0     360     .05       0
Bank Sta=109.6,150.5
XS Rating Curve= 0 ,0
Exp/Cntr(USF)=0,0
Exp/Cntr=0.3,0.1

Type RM Length L Ch R = 1 ,27510   ,474.5,440.2,422.7
XS GIS Cut Line= 2
2208557.15805679641177.1735356322208944.21870449640817.179602947
#Sta/Elev= 30
       0  2104.3    50.2 2103.14    64.6 2102.55    70.1 2101.85    75.1 2098.94
    84.2 2092.14    95.5 2080.14    99.8 2076.48     104 2074.67   113.4 2073.68
     121 2072.91   135.2 2072.63   152.7 2072.96   158.6 2073.75   166.3 2076.38
   173.5 2077.39   193.8 2077.33   208.7  2075.8   217.2  2075.9   234.9 2077.84
   245.5 2081.08   251.2  2081.8   270.2 2081.24   299.1  2081.7   337.3 2081.51
   370.1 2080.59   397.4 2078.95   452.2 2077.62   517.2 2079.66   528.6 2081.09
#Mann= 5 ,-1,0
       0     .06       0   113.4    .045       0   158.6     .06       0
     200      .1       0     470     .05       0
#XS Ineff= 2 , 0
                          338.83         2083.59
Permanent Ineff=
       F       F
Bank Sta=113.4,158.6
XS Rating Curve= 0 ,0
Exp/Cntr(USF)=0,0
Exp/Cntr=0.3,0.1

Type RM Length L Ch R = 1 ,27070   ,60.3,67,54.5
XS GIS Cut Line= 6
2208930.67280368641442.3538296242209012.52587095641443.594027613
 2209029.2685438641369.1821482812209035.46953374641282.988388055
2209009.42537598641132.3043324092208970.35913933640974.179088829
#Sta/Elev= 30
       0 2092.79    33.5 2090.64    53.5 2088.34    61.5 2085.61    69.5 2079.94
    73.5  2077.7    77.5 2076.49   104.8 2076.73   121.2 2080.44   129.4 2078.75
   141.7 2078.39   158.1 2072.31  168.692069.802   174.2 2068.52   189.6 2068.06
   202.3 2069.28   239.4 2069.11   254.5 2069.77   258.6 2071.26   270.7  2077.7
   274.8 2078.82   278.9    2079     291  2077.9   319.5 2078.14   376.3 2076.34
   429.5 2077.63   450.1 2078.75   540.8 2078.83   552.8 2079.57   560.3  2079.1
#Mann= 3 ,-1,0
       0      .1       0  168.69    .045       0   254.5      .1       0
Bank Sta=168.69,254.5
XS Rating Curve= 0 ,0
Exp/Cntr(USF)=0,0
Exp/Cntr=0.3,0.1

Type RM Length L Ch R = 1 ,27003   ,129.1,164.7,205.1
XS GIS Cut Line= 6
2208983.07116871641461.2668489542209064.92423598641462.507046943
2209081.66690883641388.0951676112209087.86789877641301.901407385
2209050.66195911641148.7369557612209009.11532648640980.070029276
#Sta/Elev= 30
       0 2088.41    17.1  2081.6    25.1 2076.45    45.1 2072.41    57.1 2072.08
    69.1 2070.57    77.1 2068.78   100.5 2069.02   112.5 2070.18   120.1 2071.63
   124.2 2071.71   136.5 2071.19   148.8 2069.12   155.52069.312   165.1 2068.39
   193.1 2069.12   237.3 2068.93   248.2 2068.46   256.8 2069.21     270 2070.25
   294.7 2071.14   317.8 2073.79     340 2074.07   350.9 2074.72   429.3 2074.34
   488.2 2074.78   517.1  2075.6   554.1 2075.84   565.8 2076.87   575.9  2076.5
#Mann= 4 ,-1,0
       0      .1       0   155.5    .045       0   256.8      .1       0
  552.17     .05       0
Bank Sta=155.5,256.8
XS Rating Curve= 0 ,0
Exp/Cntr(USF)=0,0
Exp/Cntr=0.3,0.1

Type RM Length L Ch R = 1 ,26839   ,206.6,219.5,240.8
XS GIS Cut Line= 3
2208957.76991507641497.9450152232209098.06800938641525.609428185
2209449.80125989641282.557800021
#Sta/Elev= 30
       0 2091.44    18.8 2089.06    38.9 2080.45    47.3    2074    51.4 2072.13
    67.7 2071.94    79.9 2068.58   103.6 2068.27   112.5 2071.38   141.1 2074.09
   150.6 2077.41   169.9 2072.29   190.8 2072.08   213.6 2073.83   223.4 2069.18
   242.8 2067.68   256.3 2067.02   282.8 2067.58   286.6 2068.56   296.3 2074.17
   301.1 2074.72   343.2 2073.15   359.5 2070.47   374.1  2074.9   389.2 2082.65
   397.8 2085.94   408.1 2088.25   481.5 2094.03   524.8 2099.46   570.5 2103.88
#Mann= 3 ,-1,0
       0      .1       0   242.8    .045       0   282.8      .1       0
#XS Ineff= 2 ,-1
  150.42  209.58 2079.02  302.54   570.5 2080.41
Permanent Ineff=
       F       F
Bank Sta=242.8,282.8
XS Rating Curve= 0 ,0
Exp/Cntr(USF)=0,0
Exp/Cntr=0.3,0.1

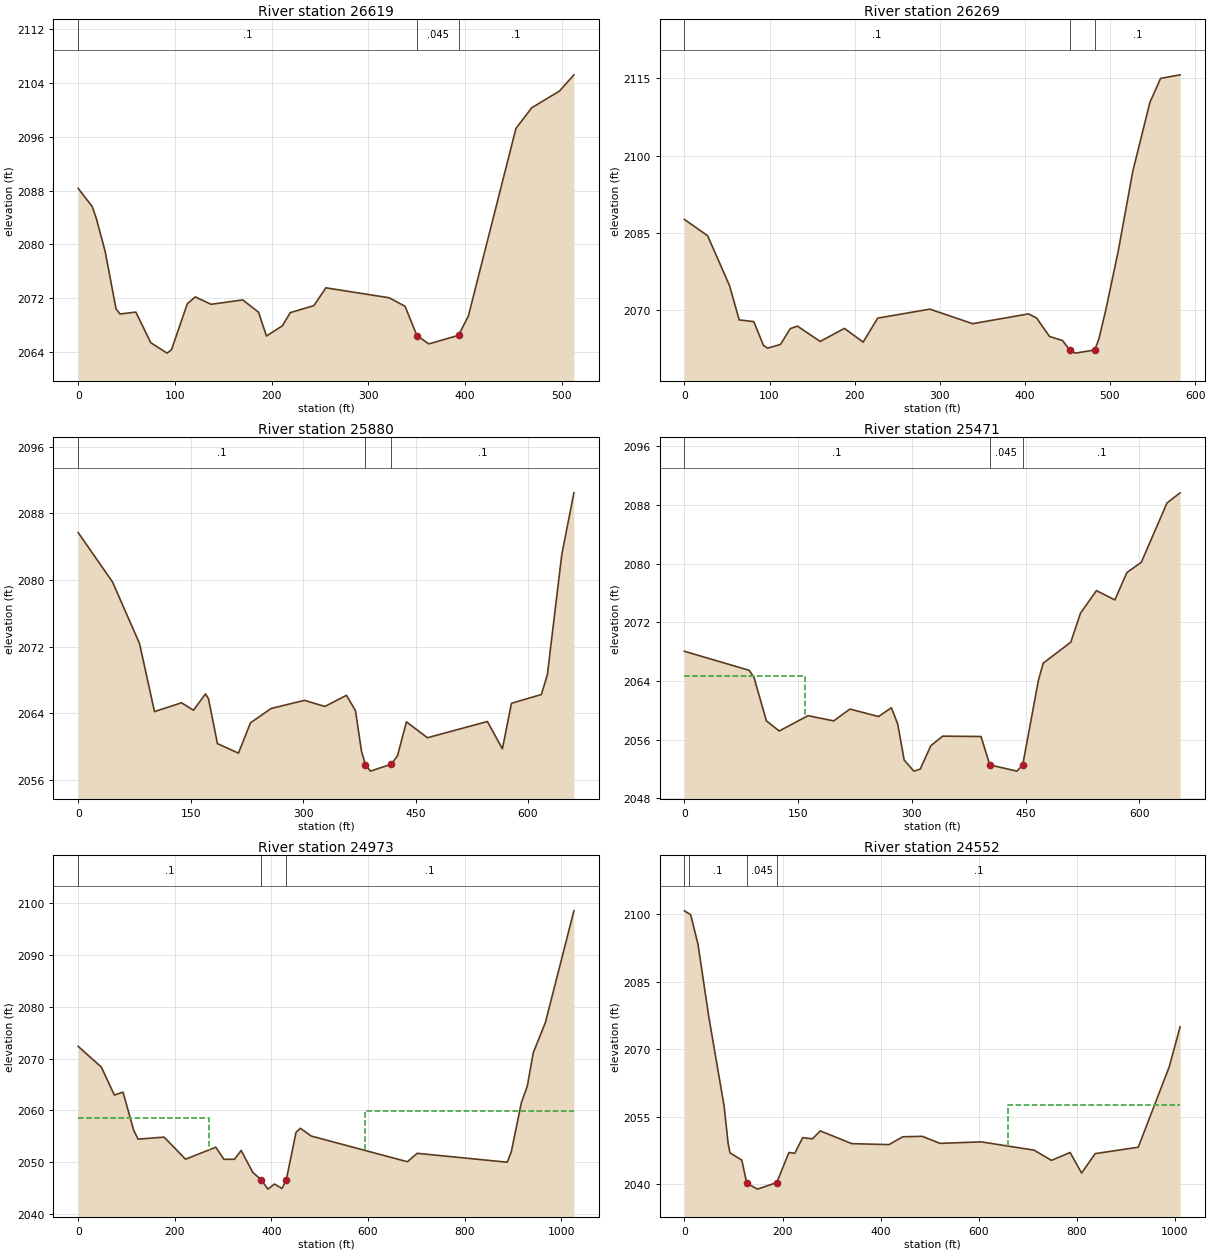
Type RM Length L Ch R = 1 ,26619   ,343.9,350.6,365.8
XS GIS Cut Line= 2
2208925.93723392641574.2173363022209426.72922606641682.496685955
#Sta/Elev= 30
       0 2088.32    14.5 2085.62    18.7 2083.88    27.9 2078.94    39.1 2070.42
    43.2 2069.65    59.6 2069.93      75 2065.38    91.9 2063.83    96.4 2064.33
   112.8 2071.17     121 2072.19   137.3 2071.09   170.1 2071.74   186.4 2069.92
   194.6 2066.38     211 2067.88   219.2 2069.85   243.7  2070.9     256 2073.54
   321.5 2072.06   337.9 2070.79   350.1 2066.45   362.4  2065.2  393.132066.476
   403.3 2069.34   452.5 2097.24   468.8 2100.31   497.5  2102.8   512.4 2105.21
#Mann= 3 ,-1,0
       0      .1       0   350.1    .045       0  393.13      .1       0
Bank Sta=350.1,393.13
XS Rating Curve= 0 ,0
Exp/Cntr(USF)=0,0
Exp/Cntr=0.3,0.1

Type RM Length L Ch R = 1 ,26269   ,384.4,389,402.4
XS GIS Cut Line= 2
2208871.79755909  641599.35361392209223.70544546642063.407969554
#Sta/Elev= 30
       0 2087.62    27.3 2084.45      53 2074.78    64.4 2068.11    81.5 2067.78
    92.9 2063.16    97.7 2062.63   112.9 2063.34   124.3 2066.41   132.8 2066.91
   159.5 2063.93     188 2066.46     210  2063.8   227.1 2068.46   288.4  2070.2
   338.6 2067.38   404.4 2069.28   413.9 2068.46     429 2064.89   444.2 2064.11
   452.7 2062.29   459.1 2061.66  481.982062.259   486.9 2064.35   495.5 2070.36
   509.8 2081.55   526.8 2096.96   546.9 2110.34   559.5 2115.01   582.4  2115.7
#Mann= 3 ,-1,0
       0      .1       0   452.7    .045       0  481.98      .1       0
Bank Sta=452.7,481.98
XS Rating Curve= 0 ,0
Exp/Cntr(USF)=0,0
Exp/Cntr=0.3,0.1

Type RM Length L Ch R = 1 ,25880   ,401,408.9,414.3
XS GIS Cut Line= 2
2208768.49052934641611.3566580732208777.13368236642272.557864187
#Sta/Elev= 30
       0 2085.68    45.8 2079.75    81.8 2072.36   101.8 2064.18   137.8 2065.24
   153.8 2064.34   169.8 2066.31   173.8 2065.73   185.8 2060.33   213.8 2059.19
   229.8 2062.83   257.5 2064.56   301.8 2065.53   329.2  2064.8   357.9 2066.14
   369.9  2064.3   377.9 2059.44   383.2 2057.81   389.9 2057.03   417.9 2057.87
   425.9 2058.86   437.9 2062.95   465.9 2061.04   545.9 2062.99   565.9 2059.71
     578 2065.18   617.9 2066.23   625.9 2068.61   645.1 2083.02   661.3 2090.46
#Mann= 3 ,-1,0
       0      .1       0   383.2    .045       0   417.9      .1       0
Bank Sta=383.2,417.9
XS Rating Curve= 0 ,0
Exp/Cntr(USF)=0,0
Exp/Cntr=0.3,0.1

Type RM Length L Ch R = 1 ,25471   ,492,497.8,499
XS GIS Cut Line= 2
2208510.22187364 641554.881738152208299.46385378642173.620879022
#Sta/Elev= 30
       0 2068.06    85.4 2065.46    91.7 2064.52   108.1 2058.58     125 2057.19
     163 2059.28   196.8 2058.57   218.3 2060.18     256 2059.16   272.9 2060.36
   281.3 2058.13   289.8 2053.23   302.5 2051.72   310.9 2051.99   324.9 2055.18
   340.5 2056.49   391.1 2056.44  402.652052.569   438.4 2051.72   446.1 2052.58
   466.8 2064.11   473.1 2066.44   509.5  2069.3   522.2 2073.24   543.3 2076.33
   567.6 2075.06   583.4 2078.79   602.5  2080.2   636.3 2088.28   653.6 2089.66
#Mann= 3 ,-1,0
       0      .1       0  402.65    .045       0   446.1      .1       0
#XS Ineff= 2 , 0
          158.64 2064.68
Permanent Ineff=
       F       F
Bank Sta=402.65,446.1
XS Rating Curve= 0 ,0
Exp/Cntr(USF)=0,0
Exp/Cntr=0.3,0.1

Type RM Length L Ch R = 1 ,24973   ,428.9,420.7,397.1
XS GIS Cut Line= 3
2208111.90855171641394.3962734862207822.04727658641969.863872266
2207922.24699266 642338.24518137
#Sta/Elev= 30
       0 2072.37    47.9 2068.36    74.8 2062.96    92.7 2063.53   115.1 2056.09
     124 2054.44   177.8 2054.83   222.3 2050.56   284.8 2052.88   301.7 2050.54
   323.6 2050.55   337.3 2052.25   361.4 2048.02  378.962046.577   392.8 2044.78
   406.2 2045.77   421.8 2044.91   430.8  2046.6     451 2055.78     460 2056.54
   482.3 2055.04   681.4 2050.07   701.7  2051.7   888.2 2049.98   896.6 2052.04
   917.2 2061.43   929.7 2064.72   942.1 2071.17     967 2076.94  1026.1 2098.56
#Mann= 3 ,-1,0
       0      .1       0  378.96    .045       0   430.8      .1       0
#XS Ineff= 2 , 0
          270.63 2058.51  592.74         2059.79
Permanent Ineff=
       F       F
Bank Sta=378.96,430.8
XS Rating Curve= 0 ,0
Exp/Cntr(USF)=0,0
Exp/Cntr=0.3,0.1

Type RM Length L Ch R = 1 ,24552   ,410.4,396.6,361.3
XS GIS Cut Line= 3
2207574.49503686 641392.241979592207587.61536346642048.991124483
2207764.71013344642354.998782775
#Sta/Elev= 30
       0 2100.79    12.9 2099.91    27.8 2093.31    49.6 2077.33      81 2057.37
      89 2049.23    92.8 2047.04     117  2045.4127.14722040.272     149 2038.96
 188.2812040.424     213 2047.09     225 2046.92     241 2050.39     261 2050.13
     277  2051.9     341 2049.07     417 2048.85     445 2050.59     485 2050.69
     521 2049.13   605.1 2049.46   712.6 2047.62   748.2 2045.35   786.2  2047.1
   809.6 2042.53   837.3 2046.85   925.1 2048.27   988.2 2066.12  1010.4 2075.02
#Mann= 4 ,-1,0
       0     .06       0      10      .1       0127.1472    .045       0
 188.281      .1       0
#XS Ineff= 2 , 0
                          660.07         2057.66
Permanent Ineff=
       F       F
Bank Sta=127.1472,188.281
XS Rating Curve= 0 ,0
Exp/Cntr(USF)=0,0
Exp/Cntr=0.3,0.1

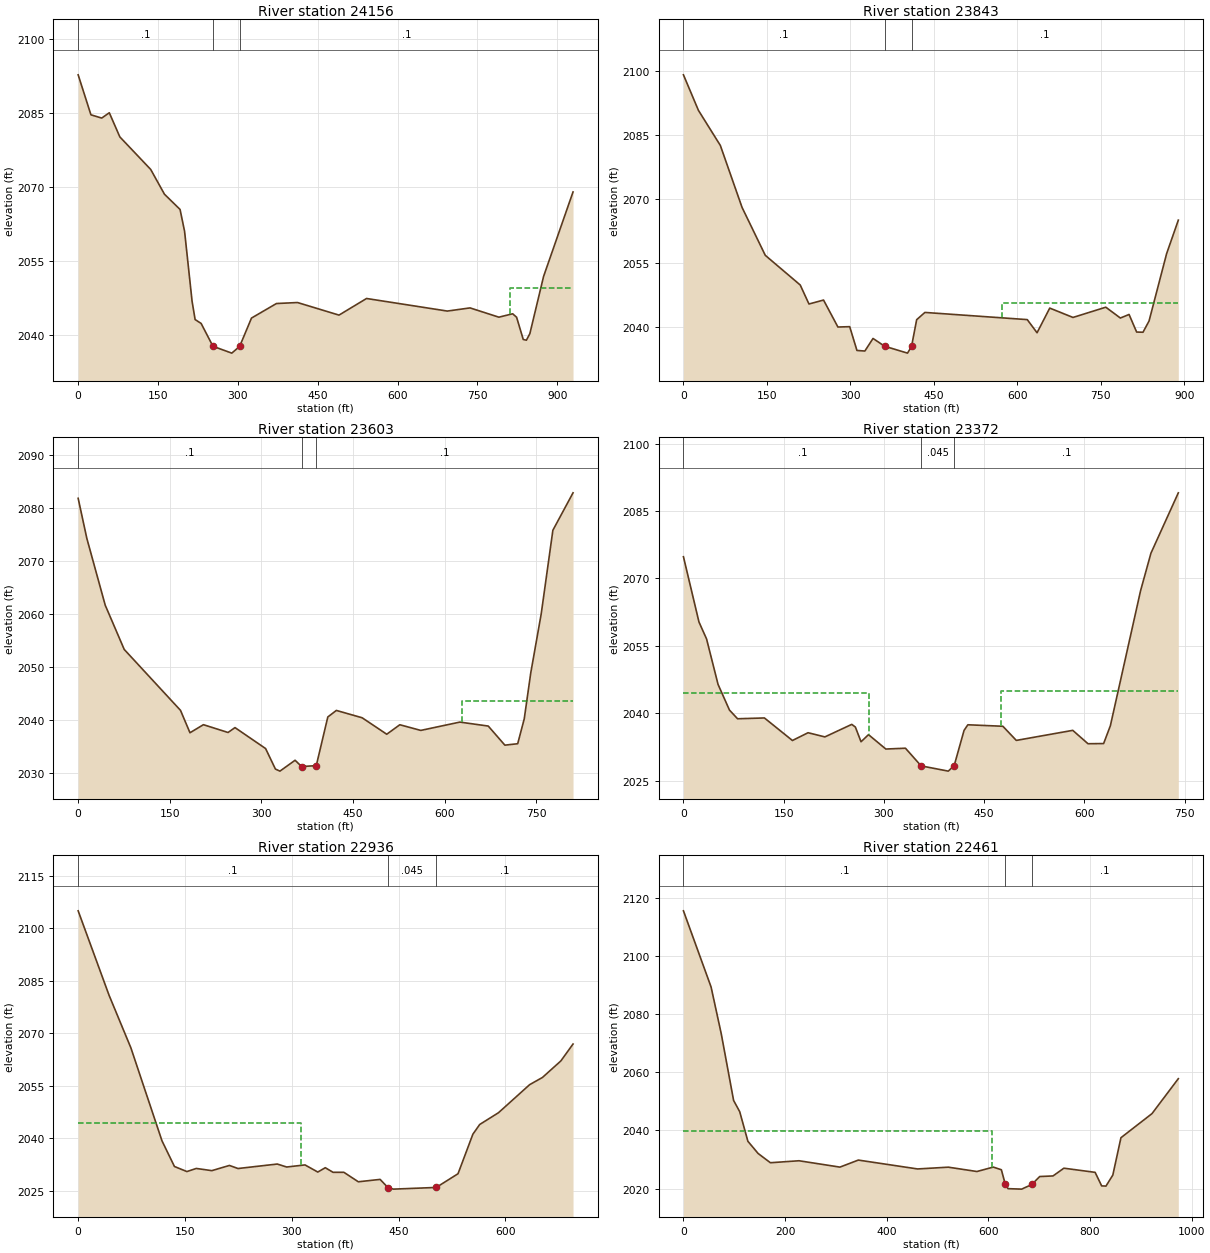
Type RM Length L Ch R = 1 ,24156   ,311.1,312.2,307.4
XS GIS Cut Line= 3
2207106.23027613641620.458844054 2207416.4669072641920.815327638
2207554.78897201642399.014465977
#Sta/Elev= 30
       0 2092.74      24 2084.63    44.3 2083.97    58.5 2085.05    78.3 2080.15
   136.3 2073.55   162.1 2068.53   191.4 2065.44   199.9 2061.02     214 2046.81
   219.7 2043.11     231 2042.32   253.2 2037.69   288.6  2036.3   303.4 2037.67
   325.6 2043.41   372.5 2046.36   412.1 2046.56     490 2044.01   541.7 2047.38
   693.5 2044.83   736.2 2045.47   790.3 2043.59   816.2 2044.28   823.6 2043.58
   836.1 2039.07     842 2038.92   848.5 2040.25   874.3 2051.86   929.6 2068.99
#Mann= 3 ,-1,0
       0      .1       0   253.2    .045       0   303.4      .1       0
#XS Ineff= 2 , 0
                          811.83         2049.41
Permanent Ineff=
       F       F
Bank Sta=253.2,303.4
XS Rating Curve= 0 ,0
Exp/Cntr(USF)=0,0
Exp/Cntr=0.3,0.1

Type RM Length L Ch R = 1 ,23843   ,238.8,239.9,241.3
XS GIS Cut Line= 2
 2206843.6265196641822.5113486242207523.85292154642395.046632183
#Sta/Elev= 30
       0 2099.19    26.9 2090.84    66.3 2082.58   105.3 2068.01     147 2056.75
   209.8 2049.77   225.5  2045.3   251.7 2046.23   277.5 2039.89   298.7 2039.97
   311.7 2034.38   325.9 2034.24   340.6  2037.2   361.5 2035.37   402.6 2033.75
  409.782035.319     419 2041.61   433.8 2043.32   617.7 2041.63   635.3 2038.54
   658.1 2044.34   699.9 2042.14   758.8 2044.55     785    2042   800.6 2042.84
   814.2 2038.71   825.6 2038.66   836.5  2041.3   868.1 2057.15   889.1 2065.02
#Mann= 3 ,-1,0
       0      .1       0   361.5    .045       0  409.78      .1       0
#XS Ineff= 2 , 0
                          572.96         2045.59
Permanent Ineff=
       F       F
Bank Sta=361.5,409.78
XS Rating Curve= 0 ,0
Exp/Cntr(USF)=0,0
Exp/Cntr=0.3,0.1

Type RM Length L Ch R = 1 ,23603   ,229.8,231,232.7
XS GIS Cut Line= 2
2206738.68878964641976.1441535622207278.14484239642580.809179726
#Sta/Elev= 30
       0 2081.79    14.2 2074.23    44.3 2061.63    75.4 2053.28   167.6 2041.78
   183.1 2037.56   205.1 2039.08   245.4 2037.61   256.8 2038.53   306.9 2034.58
     323 2030.71   330.4 2030.32   355.2 2032.37   365.9 2031.18   389.9 2031.36
   408.8 2040.54   422.8 2041.77   464.9 2040.39   505.3 2037.28   526.7 2039.07
     561    2038     625 2039.57   671.5 2038.82   698.7 2035.22   719.7 2035.49
   730.4 2040.17   741.1 2048.86   758.2 2059.98   777.3 2075.76   810.3 2082.82
#Mann= 3 ,-1,0
       0      .1       0   365.9    .045       0   389.9      .1       0
#XS Ineff= 2 , 0
                           629.3         2043.62
Permanent Ineff=
       F       F
Bank Sta=365.9,389.9
XS Rating Curve= 0 ,0
Exp/Cntr(USF)=0,0
Exp/Cntr=0.3,0.1

Type RM Length L Ch R = 1 ,23372   ,428.6,436.2,444.5
XS GIS Cut Line= 2
2206584.07127076642104.7421861562207032.67784273642694.152280723
#Sta/Elev= 30
       0 2074.84    23.2 2060.32    34.6 2056.53    51.8 2046.41    68.9 2040.69
      81 2038.76   121.2 2038.94   163.1 2033.92   186.5 2035.65   211.7 2034.72
   251.9 2037.51   257.3 2036.92   265.8 2033.64     277 2035.22   302.9 2032.02
   332.3  2032.2  355.742028.269   396.4  2027.1  405.232028.339     420 2036.17
   425.7 2037.42   478.1 2037.09   498.2 2033.94   582.7 2036.18   605.5  2033.2
   628.9 2033.24     639 2037.21   684.2 2067.27   699.7 2075.62   740.7 2089.07
#Mann= 3 ,-1,0
       0      .1       0  355.74    .045       0  405.23      .1       0
#XS Ineff= 2 , 0
          278.11 2044.57  475.25         2044.95
Permanent Ineff=
       F       F
Bank Sta=355.74,405.23
XS Rating Curve= 0 ,0
Exp/Cntr(USF)=0,0
Exp/Cntr=0.3,0.1

Type RM Length L Ch R = 1 ,22936   ,479.9,475.3,463.4
XS GIS Cut Line= 2
 2206279.5427219642245.5457087472206561.14976708642880.798810669
#Sta/Elev= 30
       0 2104.97    43.4 2080.84      74 2065.83   117.7 2039.24   135.2  2031.9
   152.7 2030.45   165.9 2031.34   187.7 2030.71   212.4  2032.2   224.5 2031.32
   279.6  2032.6   292.8 2031.75   318.5 2032.35   336.5 2030.31     347 2031.55
   357.9 2030.24   373.1 2030.24   393.4 2027.53     424 2028.21  434.922025.892
   442.8 2025.43   502.8 2025.91   533.4 2029.83   554.3 2041.14   563.9 2043.91
   590.3 2047.28     634 2055.29     652 2057.35   677.8 2062.07   694.9  2066.9
#Mann= 3 ,-1,0
       0      .1       0  434.92    .045       0   502.8      .1       0
#XS Ineff= 2 , 0
          313.42 2044.47
Permanent Ineff=
       F       F
Bank Sta=434.92,502.8
XS Rating Curve= 0 ,0
Exp/Cntr(USF)=0,0
Exp/Cntr=0.3,0.1

Type RM Length L Ch R = 1 ,22461   ,348.9,333.1,319.7
XS GIS Cut Line= 3
2205956.70563462642239.1075177372206023.56362094642845.744378826
 2206264.8374376 643117.64293748
#Sta/Elev= 30
       0 2115.53    54.4 2089.32    74.5 2073.15    98.7 2050.31   110.7 2046.45
   126.8 2036.27     147 2032.06   171.1 2028.89   227.4 2029.57   307.9 2027.38
   344.1  2029.8   460.8 2026.75   521.2 2027.36   577.5 2025.87   609.7 2027.39
   625.6 2026.47633.07042021.632   638.7 2019.97   665.5 2019.81685.58982021.408
     701 2024.14   727.2 2024.34   748.6 2027.01   810.1 2025.58   822.9 2020.93
   831.4 2020.85   844.9 2024.64   860.9 2037.49     922 2045.78   973.8  2057.8
#Mann= 3 ,-1,0
       0      .1       0633.0704    .045       0685.5898      .1       0
#XS Ineff= 2 , 0
           606.2 2039.96
Permanent Ineff=
       F       F
Bank Sta=633.0704,685.5898
XS Rating Curve= 0 ,0
Exp/Cntr(USF)=0,0
Exp/Cntr=0.3,0.1

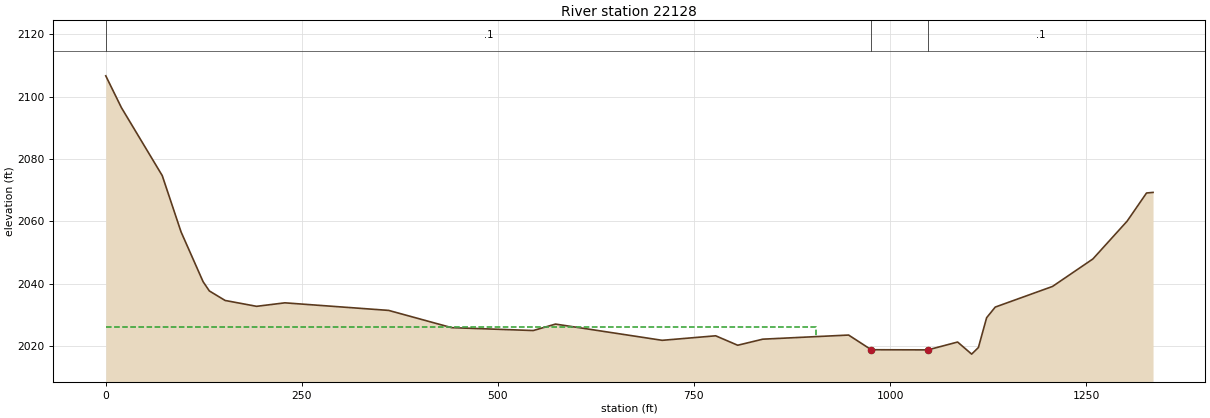
Type RM Length L Ch R = 1 ,22128   ,170.8,168.4,172.9
XS GIS Cut Line= 3
2205835.64330939642205.3635752452205772.41036547643114.337143989
2206167.61626493643268.467444776
#Sta/Elev= 30
       0 2106.67    19.9 2096.48      72 2074.65      96 2056.58   124.1  2040.6
   132.1 2037.63   152.2 2034.58   192.3  2032.7   228.4 2033.82   360.7 2031.39
   440.9 2025.86   545.1 2024.93   573.5    2027   709.5 2021.79   777.7 2023.24
   805.8 2020.21   837.8 2022.16   947.2 2023.48   976.1 2018.77  1048.3 2018.72
  1086.2 2021.24  1104.1 2017.36  1112.7 2019.48  1123.2 2029.05  1134.2 2032.46
  1207.2 2039.08  1258.7  2047.9  1302.4 2060.05  1327.1 2069.07  1335.4 2069.26
#Mann= 3 ,-1,0
       0      .1       0   976.1    .045       0  1048.3      .1       0
#XS Ineff= 2 , 0
          905.52 2025.96
Permanent Ineff=
       F       F
Bank Sta=976.1,1048.3
XS Rating Curve= 0 ,0
Exp/Cntr(USF)=0,0
Exp/Cntr=0.3,0.1