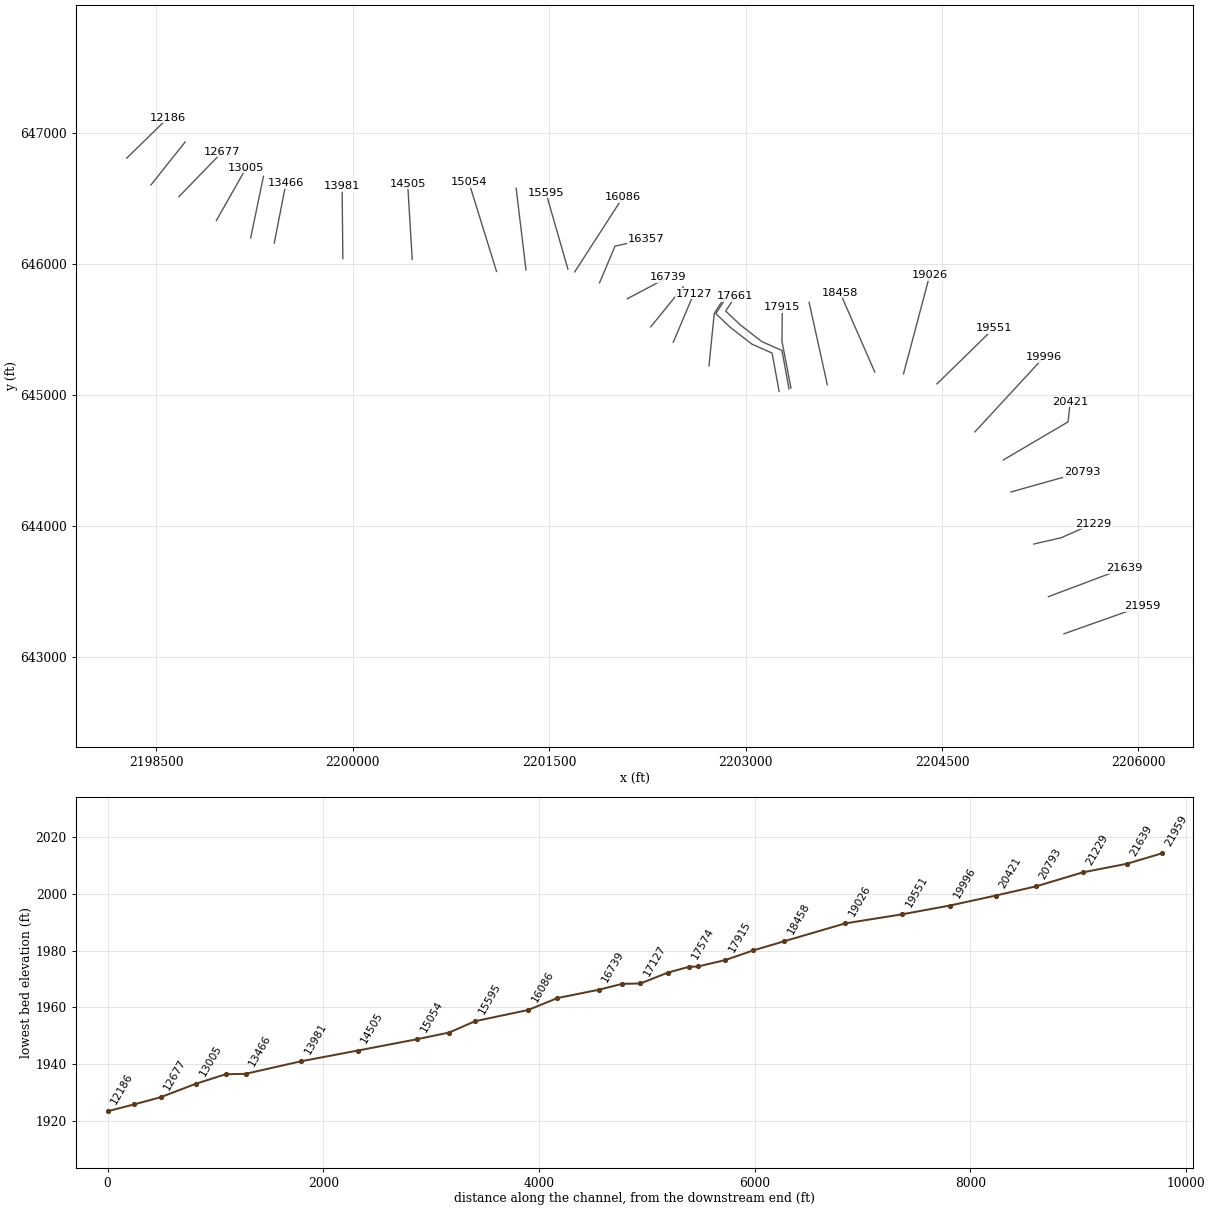
HEC-RAS study LFBUCKRV.prj: LFBUCKRV

--- LFBUCKRV.g01 (geometry) --- (continued)

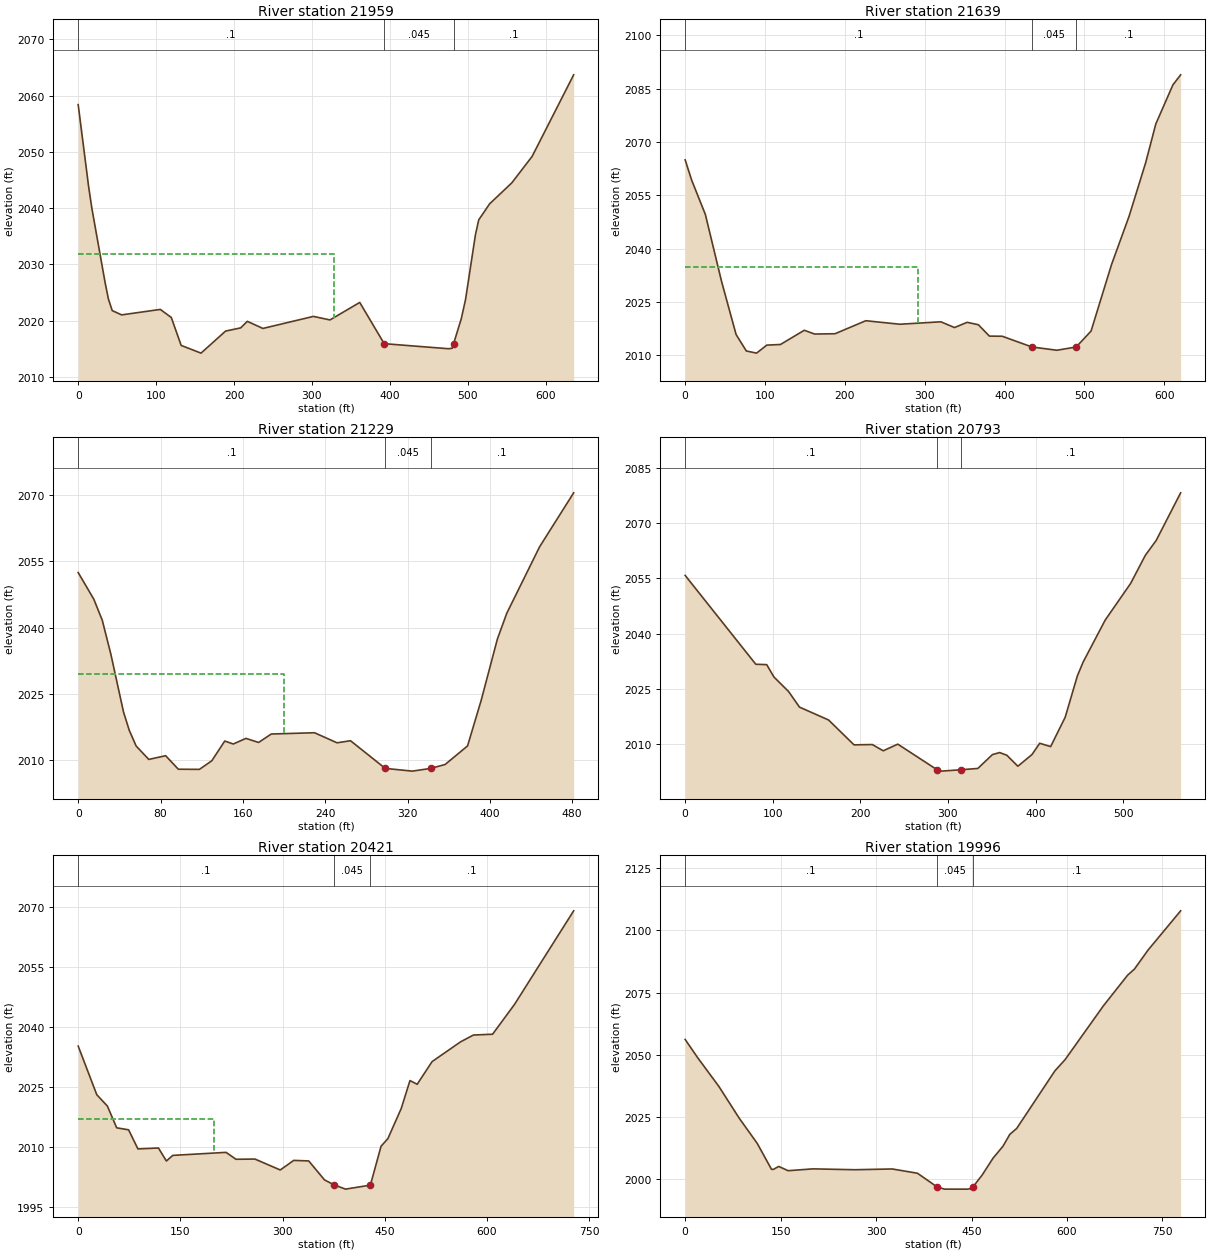
Type RM Length L Ch R = 1 ,21959   ,320.2,320,319.4
XS GIS Cut Line= 2
2205431.56443362643173.9812753442206031.00203177643386.369422007
#Sta/Elev= 30
       0 2058.38    13.4  2043.8    17.6 2039.91    34.6 2026.71    38.8 2023.82
    43.7 2021.76    55.8    2021   105.4 2021.97   119.5 2020.54   132.2 2015.57
   157.7  2014.2   189.2 2018.12   208.6 2018.69   217.1 2019.85   237.1 2018.59
   301.9 2020.73   323.2  2020.1   361.4 2023.21   392.8 2015.88   475.5 2014.98
   480.2 2015.08  481.89 2015.88   491.8 2020.35   497.2 2023.72   509.9 2035.23
   514.1 2037.88   528.1 2040.74   556.6 2044.47   582.7 2049.18     636 2063.68
#Mann= 3 ,-1,0
       0      .1       0   392.8    .045       0  481.89      .1       0
#XS Ineff= 2 , 0
          328.41 2031.84
Permanent Ineff=
       F       F
Bank Sta=392.8,481.89
XS Rating Curve= 0 ,0
Exp/Cntr(USF)=0,0
Exp/Cntr=0.3,0.1

Type RM Length L Ch R = 1 ,21639   ,405.1,410.2,410.6
XS GIS Cut Line= 2
2205312.48998752643458.0720804662205893.25679533643676.578404194
#Sta/Elev= 30
       0 2064.96     8.2 2059.22    25.3  2049.6    45.6 2030.73    63.8  2015.8
    76.6 2011.18    89.4 2010.57   102.2 2012.82   119.3    2013   149.2    2017
   162.1 2015.94   187.7 2016.03   226.2 2019.69   268.9  2018.7   320.2 2019.39
   337.3 2017.77   353.1 2019.24   367.2 2018.56     381 2015.36   397.1 2015.32
  434.28  2012.3   465.5 2011.38   489.7  2012.3   508.3 2016.77   533.9 2035.46
     556 2049.14   576.7 2064.16   589.4 2075.07   610.8 2086.06   620.5  2088.9
#Mann= 3 ,-1,0
       0      .1       0  434.28    .045       0   489.7      .1       0
#XS Ineff= 2 , 0
          292.18 2034.93
Permanent Ineff=
       F       F
Bank Sta=434.28,489.7
XS Rating Curve= 0 ,0
Exp/Cntr(USF)=0,0
Exp/Cntr=0.3,0.1

Type RM Length L Ch R = 1 ,21229   ,437.4,436.4,433.8
XS GIS Cut Line= 3
2205201.32010352643860.5837294382205409.34373576643908.183939396
2205654.39783329644016.645841728
#Sta/Elev= 30
       0 2052.48    15.2 2046.43    23.4 2041.68    31.7 2034.04      44 2020.95
    49.6 2016.78    56.3 2013.22    68.6 2010.18      85 2011.02    97.3 2007.96
   117.8 2007.93   129.8 2009.87   142.4 2014.34   150.7 2013.67     163 2014.94
   175.3 2014.02   187.6 2015.93   229.6 2016.22   251.5 2013.94   264.6 2014.41
  298.33 2008.15   324.6 2007.53   342.6 2008.15   356.5 2009.03   378.3 2013.23
   391.5 2023.52   407.3 2037.43   416.4 2043.25   448.3  2058.3   481.4 2070.52
#Mann= 3 ,-1,0
       0      .1       0  298.33    .045       0   342.6      .1       0
#XS Ineff= 2 , 0
          200.44 2029.41
Permanent Ineff=
       F       F
Bank Sta=298.33,342.6
XS Rating Curve= 0 ,0
Exp/Cntr(USF)=0,0
Exp/Cntr=0.3,0.1

Type RM Length L Ch R = 1 ,20793   ,363.6,371.8,386
XS GIS Cut Line= 2
2205026.53229085 644258.570231652205571.05093117644411.554040123
#Sta/Elev= 30
       0 2055.81    80.6 2031.65    93.1 2031.54   101.4 2028.17     118 2024.25
   130.5 2019.99   163.7 2016.49   192.8 2009.72   213.6 2009.81   226.1 2008.11
   242.7 2009.92   287.5 2002.97   292.5 2002.58   314.8 2002.95   334.1 2003.31
   350.7 2007.07     359 2007.63   367.3 2006.89   379.8 2003.91   395.9 2007.09
   404.7 2010.16   417.2 2009.25   433.8 2017.23   447.8 2028.54   454.3 2032.24
   479.5 2043.67   508.6 2053.66   525.2 2061.23   537.7 2065.33   565.6 2078.27
#Mann= 3 ,-1,0
       0      .1       0   287.5    .045       0   314.8      .1       0
Bank Sta=287.5,314.8
XS Rating Curve= 0 ,0
Exp/Cntr(USF)=0,0
Exp/Cntr=0.3,0.1

Type RM Length L Ch R = 1 ,20421   ,417.7,425,433.7
XS GIS Cut Line= 3
2204968.63622814644503.4184726512205462.76818092644794.646000377
 2205479.4779571644947.421096888
#Sta/Elev= 30
       0  2035.2    27.3 2023.01    42.9 2020.16    56.5 2014.72      74 2014.22
    87.7 2009.43   117.8 2009.66   129.5 2006.41   138.8 2007.81   217.1 2008.57
   231.6 2006.84   259.5 2006.89   296.6 2004.16   316.4 2006.56   338.4 2006.42
   361.6 2001.67   375.6 2000.43   392.4 1999.36   428.9 2000.36   444.6 2010.12
   454.5 2011.98   474.2 2019.56     487 2026.55   497.6 2025.63   519.5 2031.31
   561.3 2036.26   580.1 2037.96   608.3 2038.17   640.5 2045.64   727.3 2069.08
#Mann= 3 ,-1,0
       0      .1       0   375.6    .045       0   428.9      .1       0
#XS Ineff= 2 , 0
          199.66 2016.81
Permanent Ineff=
       F       F
Bank Sta=375.6,428.9
XS Rating Curve= 0 ,0
Exp/Cntr(USF)=0,0
Exp/Cntr=0.3,0.1

Type RM Length L Ch R = 1 ,19996   ,447.8,445.5,444.1
XS GIS Cut Line= 2
2204751.43300889644718.1629676852205279.29483845645290.496672993
#Sta/Elev= 30
       0 2056.12    19.6  2048.8    53.1 2037.16    84.8 2024.47   113.2 2014.29
   135.7 2003.82   138.5 2003.79     147 2004.98   161.9 2003.27   200.8 2004.01
   266.6 2003.66   325.4 2003.97     365 2002.25  395.391996.826   407.5 1995.85
   444.3 1995.85   449.9 1996.17   452.7 1996.87   466.9  2001.6   483.9 2008.35
   499.3 2013.08   510.2 2017.92     521 2020.29   580.9 2043.44     597 2047.99
   657.1 2069.62   695.2 2081.98   706.1 2084.49   727.3 2092.09   778.6 2107.92
#Mann= 3 ,-1,0
       0      .1       0  395.39    .045       0   452.7      .1       0
Bank Sta=395.39,452.7
XS Rating Curve= 0 ,0
Exp/Cntr(USF)=0,0
Exp/Cntr=0.3,0.1

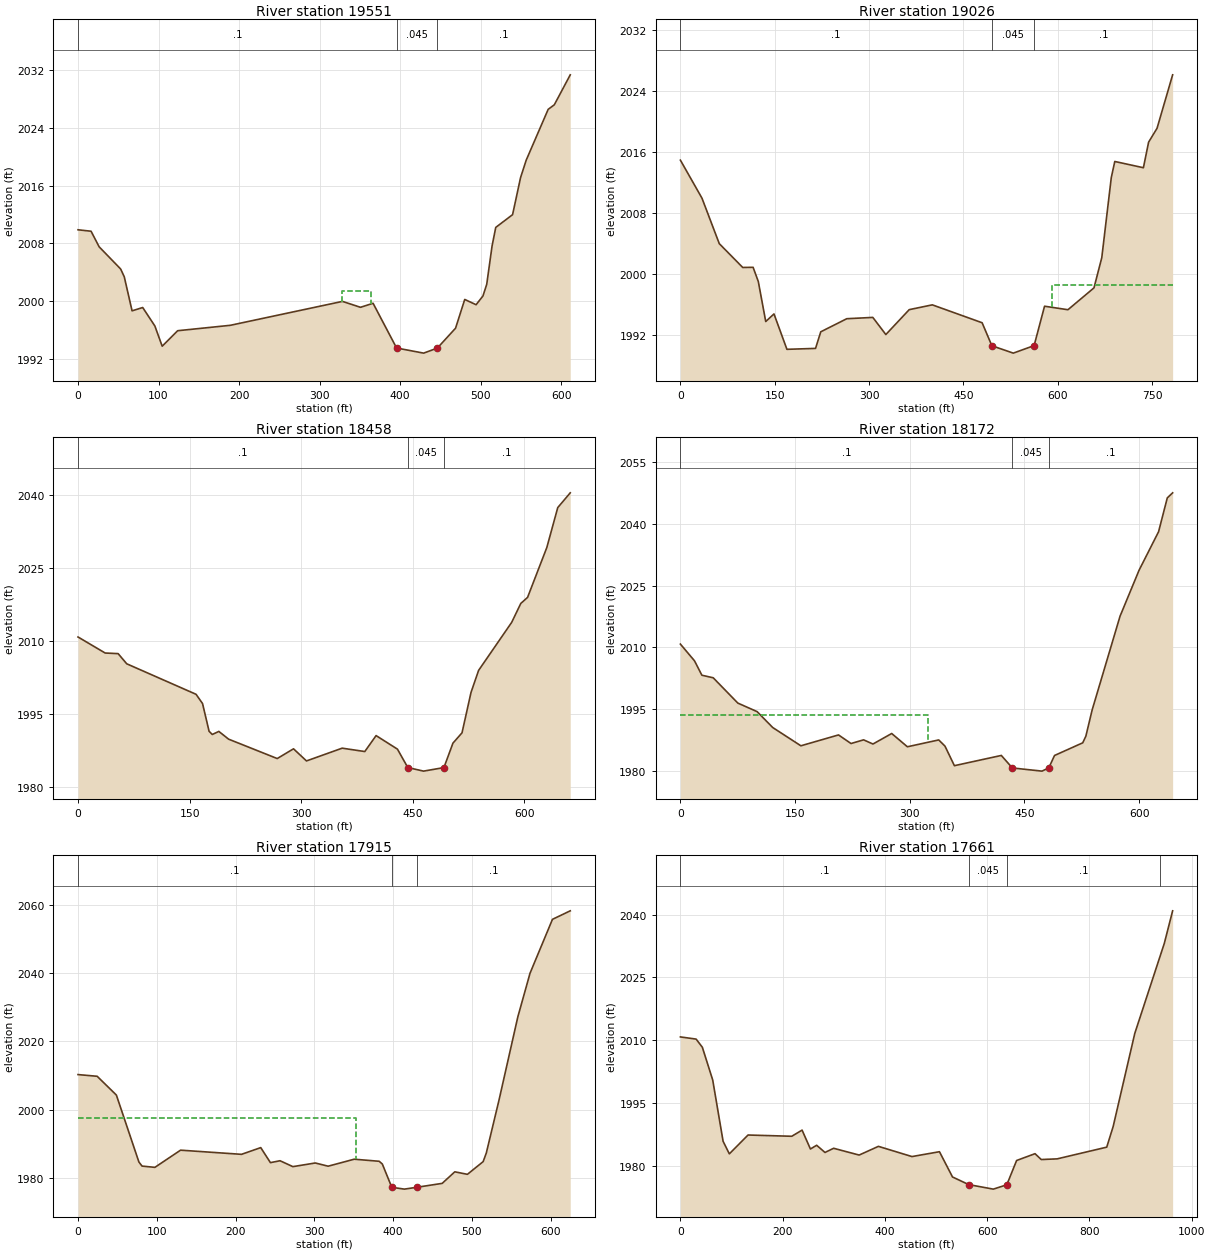
Type RM Length L Ch R = 1 ,19551   ,506.1,524.4,539.1
XS GIS Cut Line= 2
2204461.44677883645085.0380392932204898.28807041 645512.33088735
#Sta/Elev= 30
       0 2009.87    16.2 2009.67    26.2 2007.51    52.9 2004.43    57.4 2003.35
    67.1 1998.62    80.3 1999.08    95.4 1996.52   104.5 1993.71   123.7 1995.86
     189 1996.61   328.3 1999.93   350.7 1999.11   366.3 1999.67   395.5 1993.46
   429.1 1992.75   446.1 1993.45   468.7 1996.21   480.1  2000.2   494.2 1999.47
   502.7 2000.68   507.4  2002.3     514  2007.6   518.6  2010.2   539.5 2011.97
   549.4 2017.11   556.4 2019.53   583.7 2026.59   591.3 2027.22   611.1 2031.38
#Mann= 3 ,-1,0
       0      .1       0   395.5    .045       0   446.1      .1       0
#XS Ineff= 1 ,-1
   327.4  363.19 2001.31
Permanent Ineff=
       F
Bank Sta=395.5,446.1
XS Rating Curve= 0 ,0
Exp/Cntr(USF)=0,0
Exp/Cntr=0.3,0.1

Type RM Length L Ch R = 1 ,19026   ,546.3,568.1,586.1
XS GIS Cut Line= 2
2204206.02591434645161.4255875492204406.54322852645918.139737459
#Sta/Elev= 30
       0 2014.91    34.3 2009.92    61.8 2003.95    99.1 2000.82   115.6 2000.84
   123.9 1998.97   135.7 1993.72   148.8 1994.72   169.4 1990.07   214.9 1990.19
   223.2 1992.37   264.6 1994.09     306 1994.26   326.7 1992.01   363.9 1995.28
   400.6 1995.91   479.8 1993.56  495.331990.539   529.4 1989.57   562.5 1990.56
   579.1 1995.73   616.3 1995.27   657.7 1998.14   670.1  2002.1   685.2 2012.61
   690.8 2014.74   736.3 2013.92   744.6 2017.28     758  2019.1   782.8 2026.12
#Mann= 3 ,-1,0
       0      .1       0  495.33    .045       0   562.5      .1       0
#XS Ineff= 2 , 0
                          590.87         1998.56
Permanent Ineff=
       F       F
Bank Sta=495.33,562.5
XS Rating Curve= 0 ,0
Exp/Cntr(USF)=0,0
Exp/Cntr=0.3,0.1

Type RM Length L Ch R = 1 ,18458   ,290.3,286.3,280.8
XS GIS Cut Line= 2
2203986.41171311645175.748252847 2203721.4424051645782.074417128
#Sta/Elev= 30
       0 2010.78    36.5 2007.49    53.9 2007.37    65.5 2005.28   158.7 1999.02
   167.4 1997.12   176.2 1991.43   180.5 1990.78   189.3 1991.41   202.4 1989.82
   267.8 1985.84   289.7 1987.84   307.1 1985.35   355.1 1987.97   385.5 1987.28
   400.7 1990.55   429.4 1987.77   443.3    1984   464.5 1983.26   491.9 1983.99
     504    1989   516.2 1991.12   528.3 1999.41   538.5 2003.93     583 2013.79
   595.2 2017.66   604.3  2018.9   630.2 2029.14   644.9 2037.33   661.7 2040.36
#Mann= 3 ,-1,0
       0      .1       0   443.3    .045       0   491.9      .1       0
Bank Sta=443.3,491.9
XS Rating Curve= 0 ,0
Exp/Cntr(USF)=0,0
Exp/Cntr=0.3,0.1

Type RM Length L Ch R = 1 ,18172   ,261.8,257.1,256
XS GIS Cut Line= 2
2203623.74855553645079.2376109992203485.02594954645708.026993281
#Sta/Elev= 30
       0 2010.82    18.4 2006.78    28.1 2003.28    42.9 2002.66    75.1 1996.53
   100.3 1994.46   120.8  1990.6   157.6 1986.18   206.8 1988.81   223.2 1986.73
   239.6 1987.62   251.9 1986.61   276.4 1989.16   296.9 1985.94   337.9  1987.6
   346.1  1986.1   358.4 1981.36   419.8 1983.84   434.2 1980.81     473 1980.04
   481.9 1980.83   489.4 1983.83   526.3  1986.9   530.4 1988.52   538.6 1994.86
   575.1 2017.58     600 2028.73   625.5 2038.05   636.9 2046.25   643.9 2047.48
#Mann= 3 ,-1,0
       0      .1       0   434.2    .045       0   481.9      .1       0
#XS Ineff= 2 , 0
          324.17  1993.6
Permanent Ineff=
       F       F
Bank Sta=434.2,481.9
XS Rating Curve= 0 ,0
Exp/Cntr(USF)=0,0
Exp/Cntr=0.3,0.1

Type RM Length L Ch R = 1 ,17915   ,232.3,253.7,293.1
XS GIS Cut Line= 3
2203346.30334356645053.3081519362203277.59027704645411.134687007
2203280.18322294645671.725750592
#Sta/Elev= 30
       0 2010.28    24.3 2009.78    48.7 2004.27    77.3 1984.63    81.3 1983.43
    97.6 1983.06   130.2  1988.1   207.6 1986.88     232 1988.85   244.3 1984.44
   256.5    1985   272.8 1983.27   301.3 1984.34   317.6  1983.4   350.7 1985.45
   382.4 1984.84   386.4 1984.03   398.4 1977.21   414.4 1976.67   430.4 1977.22
   462.4 1978.36   478.4 1981.75   494.4 1981.01   514.4 1984.74   518.4 1987.26
   534.4 2002.65   558.4 2027.18   573.9    2040   602.4 2055.83     625 2058.33
#Mann= 3 ,-1,0
       0      .1       0   398.4    .045       0   430.4      .1       0
#XS Ineff= 2 , 0
          352.96 1997.55
Permanent Ineff=
       F       F
Bank Sta=398.4,430.4
XS Rating Curve= 0 ,0
Exp/Cntr(USF)=0,0
Exp/Cntr=0.3,0.1

Type RM Length L Ch R = 1 ,17661   ,75.4,87.3,74.9
XS GIS Cut Line= 6
2203331.23026911645047.020338464 2203277.6667951645340.209880366
2203122.61463352645409.278570526 2202957.6955162645537.548995109
2202847.74943799645641.8568129012202921.04682346645754.622021325
#Sta/Elev= 30
       0 2010.77    30.7 2010.25    42.9  2008.3    63.2 2000.47    83.5 1985.83
    95.7 1982.83   132.3 1987.33   217.8 1987.03     238  1988.5   254.3 1983.99
   266.5 1984.88   282.8 1983.16   299.7 1984.16   349.6 1982.54   387.3 1984.62
   452.9 1982.18   506.7 1983.34   532.2 1977.31  563.861975.484     612  1974.4
  638.441975.436   657.6 1981.24   693.6 1982.87   705.8 1981.47   736.9 1981.63
   833.9 1984.43   846.5 1989.38   888.8 2011.63   946.5 2033.12   962.8  2040.9
#Mann= 4 ,-1,0
       0      .1       0  563.86    .045       0  638.44      .1       0
  938.26     .08       0
Bank Sta=563.86,638.44
XS Rating Curve= 0 ,0
Exp/Cntr(USF)=0,0
Exp/Cntr=0.3,0.1

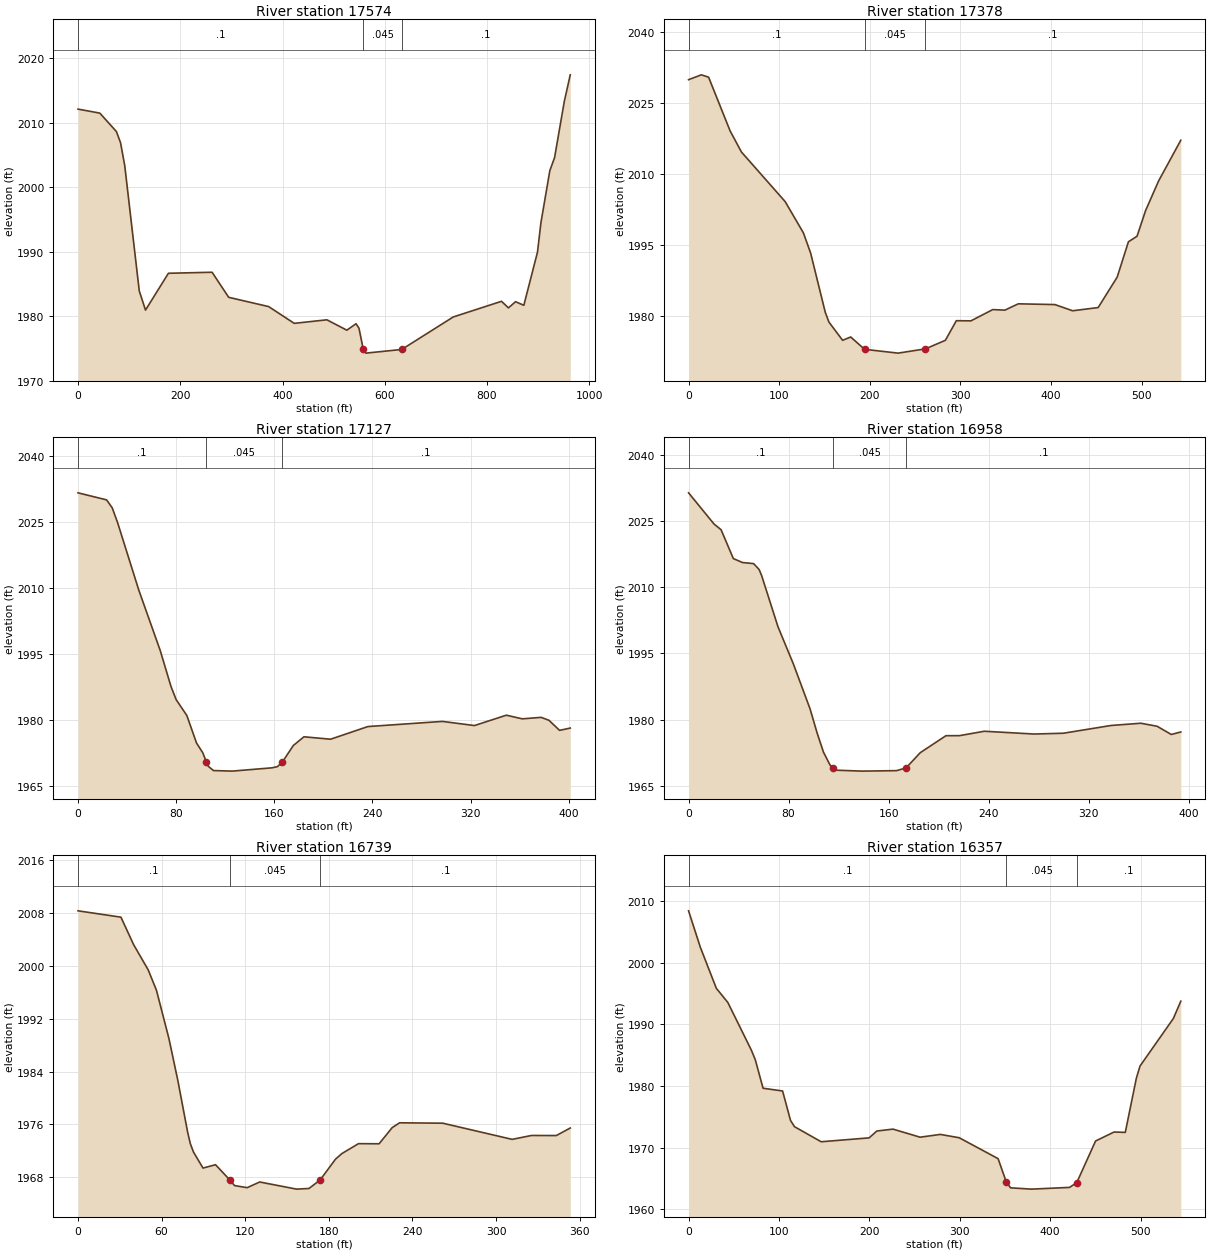
Type RM Length L Ch R = 1 ,17574   ,238.8,195.1,171.2
XS GIS Cut Line= 6
2203255.81853597 645027.286426992203202.25506197645320.475968892
2203047.20290039645389.5446590522202882.28378307645517.815083634
2202772.33770485645622.1229014272202845.63509033645734.888109851
#Sta/Elev= 30
       0 2012.12    42.6  2011.5    75.1 2008.64    83.2  2006.9    91.4 2003.34
   119.8 1983.91     132 1980.94   176.8 1986.65   262.2 1986.81   294.7 1982.92
   372.9 1981.48   422.9 1978.88   486.8 1979.43   525.8 1977.82   543.8 1978.82
   549.5 1978.14     558 1974.84   562.8 1974.26  633.111974.825   733.9 1979.87
   828.3  1982.3   841.9 1981.28   855.8 1982.24     872 1981.68   898.7 1989.92
   905.5 1994.52   922.9 2002.59   932.1 2004.58   951.2 2013.33   962.8 2017.44
#Mann= 3 ,-1,0
       0      .1       0     558    .045       0  633.11      .1       0
Bank Sta=558,633.11
XS Rating Curve= 0 ,0
Exp/Cntr(USF)=0,0
Exp/Cntr=0.3,0.1

Type RM Length L Ch R = 1 ,17378   ,265.8,251.9,246.4
XS GIS Cut Line= 3
2202720.10690718  645223.14610882202760.29756873645623.756251325
2202836.78947296645741.735290063
#Sta/Elev= 30
       0 2029.99    14.1 2031.02    22.1 2030.52    45.8 2019.19    58.3 2014.72
   106.6 2004.23   126.7 1997.63   134.7 1993.36   150.8 1980.87   154.8  1978.8
     170 1974.92   178.9 1975.62   194.3 1973.01   231.2 1972.21   261.4 1973.11
   283.4 1974.92   295.5 1979.06   311.6 1979.03   335.7 1981.41     349 1981.29
   363.9 1982.63   404.3 1982.47   423.8 1981.16     452 1981.84     473 1988.27
   485.4 1995.74   494.9 1996.91   504.4 2002.36   518.7 2008.59   543.2  2017.2
#Mann= 3 ,-1,0
       0      .1       0   194.3    .045       0   261.4      .1       0
Bank Sta=194.3,261.4
XS Rating Curve= 0 ,0
Exp/Cntr(USF)=0,0
Exp/Cntr=0.3,0.1

Type RM Length L Ch R = 1 ,17127   ,179.5,168.6,162.3
XS GIS Cut Line= 2
2202447.36333993645403.4392198842202603.36862273645773.220077079
#Sta/Elev= 30
       0 2031.56    23.3 2029.96    27.9 2028.14    32.3 2024.77    49.6 2009.44
      67  1995.8    75.7 1987.71      80 1984.64    88.7 1981.05    96.6  1974.8
   101.7 1972.59104.69991970.466   106.1 1969.54   110.4 1968.55   125.6 1968.42
   158.2 1969.17   162.5 1969.43166.48991970.432   175.5 1974.23   184.2 1976.21
   205.9 1975.66   236.3 1978.53   297.1  1979.7   323.2 1978.76   349.2 1981.11
   362.2 1980.28   377.5 1980.62   383.9 1979.96   392.6 1977.67   401.3 1978.19
#Mann= 3 ,-1,0
       0      .1       0104.6999    .045       0166.4899      .1       0
Bank Sta=104.6999,166.4899
XS Rating Curve= 0 ,0
Exp/Cntr(USF)=0,0
Exp/Cntr=0.3,0.1

Type RM Length L Ch R = 1 ,16958   ,235.2,219.4,210.7
XS GIS Cut Line= 2
2202275.41668425645521.3348880262202523.26732153645827.058656571
#Sta/Elev= 30
       0 2031.46    20.3  2024.4      26 2023.08    35.8 2016.54    43.1 2015.64
      52 2015.39    56.4 2014.06    58.4  2012.7    71.5 2001.06    83.8 1992.62
    97.1 1982.46   102.8 1976.94   107.9 1972.58   113.1 1969.68   115.5 1968.91
   118.2  1968.5   138.8 1968.29   166.3  1968.4   173.9 1969.01   185.2 1972.46
   205.8 1976.33   216.6 1976.34   236.5 1977.34   276.3 1976.71   299.7 1976.89
   337.8 1978.65   361.6 1979.16   374.6 1978.48     386 1976.61   393.6 1977.18
#Mann= 3 ,-1,0
       0      .1       0   115.5    .045       0   173.9      .1       0
Bank Sta=115.5,173.9
XS Rating Curve= 0 ,0
Exp/Cntr(USF)=0,0
Exp/Cntr=0.3,0.1

Type RM Length L Ch R = 1 ,16739   ,390.8,381.4,371.6
XS GIS Cut Line= 2
2202096.96363021645736.2628708792202409.02448212645901.907413425
#Sta/Elev= 30
       0 2008.36    30.8  2007.4    39.9 2003.24    50.4  1999.4    56.3 1996.32
    65.2 1989.05    71.6  1982.7    78.7  1974.8    80.6 1973.08    82.9  1971.8
    89.7 1969.38    98.7 1969.89109.20971967.522   112.3 1966.73   121.4 1966.41
   130.4 1967.27   156.9 1966.19   165.8 1966.29173.88371967.605   184.8 1970.73
   189.4 1971.58   201.3 1973.08   216.1 1973.06   225.5 1975.51   230.8 1976.24
   261.8 1976.18   311.6 1973.73   325.5 1974.32   343.3 1974.31   353.3 1975.45
#Mann= 3 ,-1,0
       0      .1       0109.2097    .045       0173.8837      .1       0
Bank Sta=109.2097,173.8837
XS Rating Curve= 0 ,0
Exp/Cntr(USF)=0,0
Exp/Cntr=0.3,0.1

Type RM Length L Ch R = 1 ,16357   ,251.4,271.5,291.1
XS GIS Cut Line= 3
2201883.91517576645857.213453151 2202002.4769456 646138.24875943
2202236.17993691646190.649427458
#Sta/Elev= 30
       0 2008.41      13 2002.51    30.7 1995.85    43.4 1993.56    69.4 1985.84
    73.8 1984.27    82.4 1979.65     104  1979.2   112.8 1974.42   117.2 1973.41
   146.7 1970.97   199.7  1971.6   208.3 1972.71   226.1 1973.02   256.1 1971.71
   278.5 1972.16   299.4 1971.62   342.4 1968.23351.44671964.457   356.2  1963.5
   379.2 1963.29   421.5 1963.57429.4738 1964.36   450.2 1971.09   470.7 1972.55
   483.1 1972.49   495.3 1981.25   499.4 1983.25   536.3 1990.96   544.5 1993.76
#Mann= 3 ,-1,0
       0      .1       0351.4467    .045       0429.4738      .1       0
Bank Sta=351.4467,429.4738
XS Rating Curve= 0 ,0
Exp/Cntr(USF)=0,0
Exp/Cntr=0.3,0.1

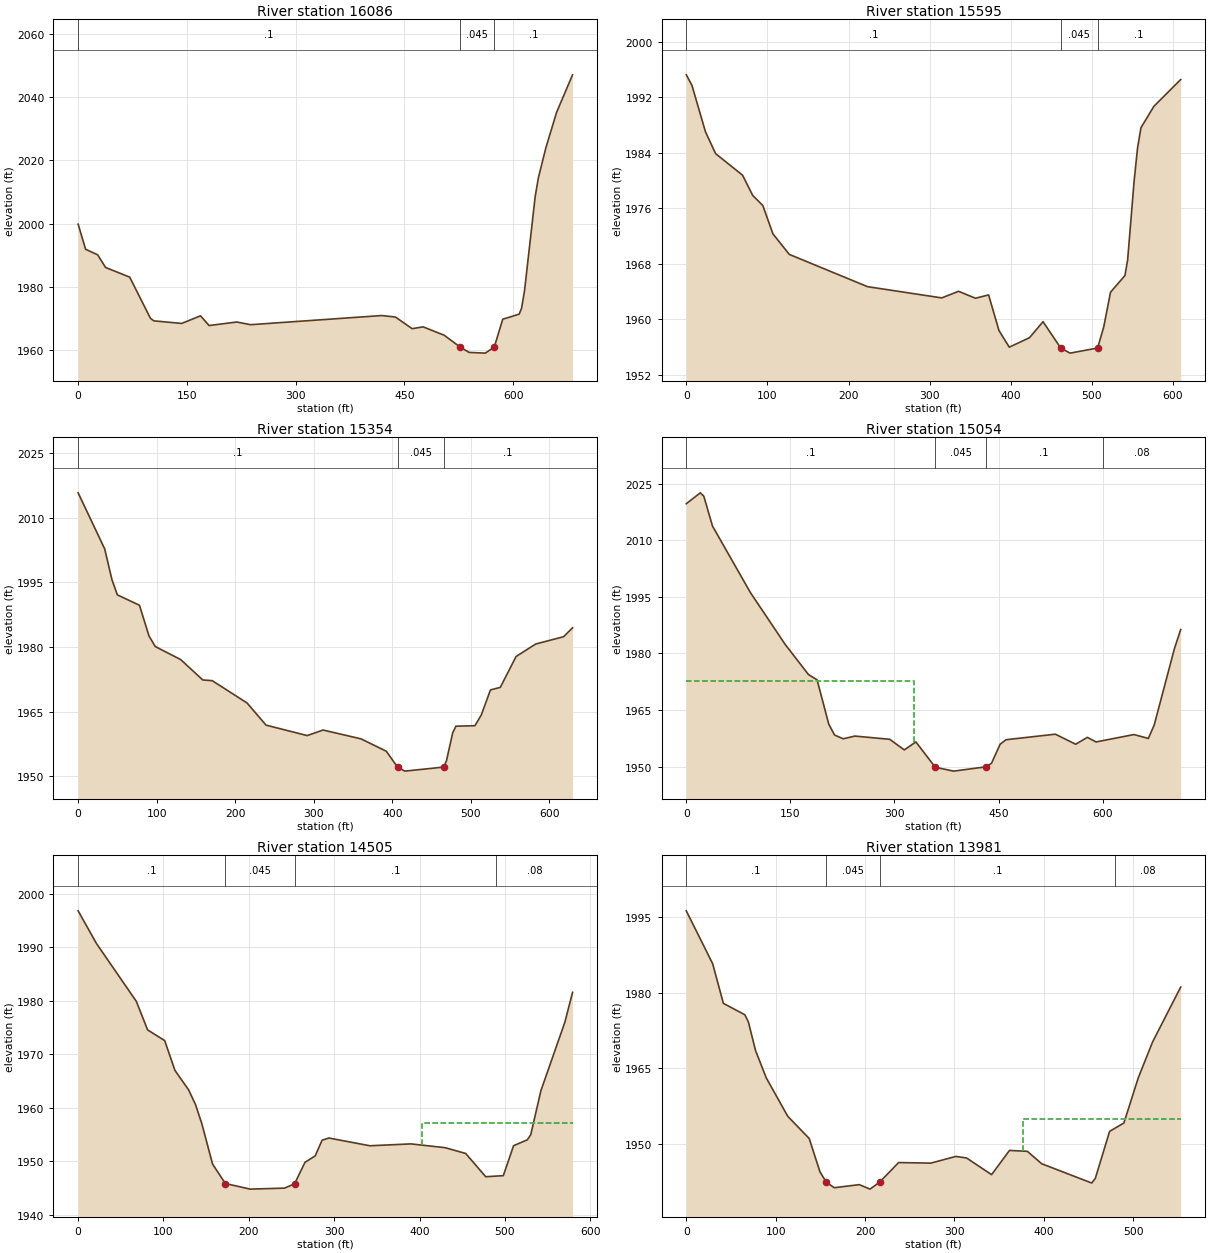
Type RM Length L Ch R = 1 ,16086   ,469.7,490.6,509.1
XS GIS Cut Line= 2
2201694.59680123645941.3921248492202064.09159288646514.433170145
#Sta/Elev= 30
       0 1999.81    10.3 1991.89      27 1990.12    37.8 1986.14    71.1 1983.08
    99.7 1970.09   104.5 1969.27   142.8 1968.46   168.8 1970.86   180.6 1967.79
   218.7 1968.91   237.7 1968.06   418.6 1970.95   437.6 1970.48   460.6  1966.8
   475.7 1967.38   504.8 1964.73     527 1960.96   539.2 1959.31   561.4 1959.08
   573.9    1961   585.5 1969.78   608.2 1971.39   611.5 1973.26   615.6 1978.85
   630.3 2008.57   634.7 2014.48   645.1    2024   659.8 2035.13   681.8 2046.98
#Mann= 3 ,-1,0
       0      .1       0     527    .045       0   573.9      .1       0
Bank Sta=527,573.9
XS Rating Curve= 0 ,0
Exp/Cntr(USF)=0,0
Exp/Cntr=0.3,0.1

Type RM Length L Ch R = 1 ,15595   ,245.8,241.5,237.9
XS GIS Cut Line= 2
2201642.57707363645962.4893692612201474.35736971646548.357993275
#Sta/Elev= 30
       0 1995.26       7 1993.74    23.6 1987.07    36.1 1983.91    69.4 1980.79
    81.9 1977.88    94.4 1976.42   106.8 1972.34     127 1969.38   223.4 1964.73
   314.9 1963.11   335.7 1964.06   356.5 1963.06   372.7 1963.54   385.5  1958.4
   398.2 1956.01   423.1 1957.37   439.8 1959.68  461.691955.874   473.1 1955.15
  507.091955.887   514.7 1958.96     523 1963.93   540.8 1966.34   544.1 1968.59
   552.1 1979.97   556.3  1984.7   560.5 1987.63   576.4 1990.71   609.5 1994.58
#Mann= 3 ,-1,0
       0      .1       0  461.69    .045       0  507.09      .1       0
Bank Sta=461.69,507.09
XS Rating Curve= 0 ,0
Exp/Cntr(USF)=0,0
Exp/Cntr=0.3,0.1

Type RM Length L Ch R = 1 ,15354   ,292.2,299.1,303.8
XS GIS Cut Line= 2
2201322.50906368645955.6533273342201247.31363239646580.553290756
#Sta/Elev= 30
       0 2015.76    33.8 2002.75      43 1995.63    49.9 1992.08    78.1 1989.66
    90.2 1982.54    98.2 1980.08   130.5 1977.06   158.7 1972.32   170.7 1972.16
   215.1 1966.97   239.2 1961.84   291.6 1959.41   311.8  1960.7   360.1 1958.65
   392.3 1955.78   406.7 1952.08   415.9 1951.16  465.53  1952.1   468.9 1953.56
   476.9  1960.1     481 1961.59   505.1  1961.7   513.2 1964.18   524.9 1970.01
   537.4  1970.6   557.5 1977.76   582.4 1980.66     618 1982.36   629.4 1984.43
#Mann= 3 ,-1,0
       0      .1       0   406.7    .045       0  465.53      .1       0
Bank Sta=406.7,465.53
XS Rating Curve= 0 ,0
Exp/Cntr(USF)=0,0
Exp/Cntr=0.3,0.1

Type RM Length L Ch R = 1 ,15054   ,557.8,549.3,539.8
XS GIS Cut Line= 2
2201097.31320574645945.0873309242200886.55518588646625.700385884
#Sta/Elev= 30
       0 2019.73    20.2 2022.62    25.2 2021.75    37.8  2013.8    92.2 1996.22
   142.5 1982.41     176 1974.43   188.5 1973.01   205.3 1961.27   213.7 1958.36
   226.2 1957.37     243 1958.09   293.2 1957.23   314.2 1954.42   330.9 1956.54
  358.841949.819   385.3 1948.79   431.4 1949.92   439.8 1950.85   452.3 1955.92
   460.7 1957.12   531.9 1958.59   561.2 1955.92     578 1957.75   590.5 1956.53
     645 1958.49   665.9 1957.47   674.3 1961.01   703.6 1981.36   712.5 1986.35
#Mann= 4 ,-1,0
       0      .1       0  358.84    .045       0   431.4      .1       0
     600     .08       0
#XS Ineff= 2 , 0
          328.56 1972.82
Permanent Ineff=
       F       F
Bank Sta=358.84,431.4
XS Rating Curve= 0 ,0
Exp/Cntr(USF)=0,0
Exp/Cntr=0.3,0.1

Type RM Length L Ch R = 1 ,14505   ,524.3,524.5,521.5
XS GIS Cut Line= 2
2200453.43778727 646035.96464224 2200418.6337106646614.099026992
#Sta/Elev= 30
       0 1996.85    21.3 1990.78    68.2 1979.91    81.4 1974.58   101.4 1972.58
   113.4 1967.01   129.4 1963.37   137.5 1960.62   144.9 1957.05   157.5 1949.48
  172.481945.848   201.6  1944.8   241.7 1944.99  253.53 1945.78   265.7  1949.8
   277.7 1951.02   285.8 1953.95   293.7 1954.36   341.8 1952.91   389.9 1953.26
     430 1952.55     454 1951.47   477.5 1947.12   498.1 1947.32   510.1 1952.92
   526.2 1954.02   530.2 1954.96   542.2 1963.24   570.2 1976.02   579.2  1981.6
#Mann= 4 ,-1,0
       0      .1       0  172.48    .045       0  253.53      .1       0
     490     .08       0
#XS Ineff= 2 , 0
                           403.3         1957.23
Permanent Ineff=
       F       F
Bank Sta=172.48,253.53
XS Rating Curve= 0 ,0
Exp/Cntr(USF)=0,0
Exp/Cntr=0.3,0.1

Type RM Length L Ch R = 1 ,13981   ,513.8,514.4,506.1
XS GIS Cut Line= 2
 2199923.6423979  646043.69888152199917.84171845646596.696988655
#Sta/Elev= 30
       0 1996.26    29.5 1985.77    41.5  1977.9    65.5 1975.64    69.5  1974.2
    77.5 1968.52    89.5  1963.1   113.5 1955.49   137.5 1951.08   149.5 1944.49
  156.49 1942.44   165.5 1941.32   193.5 1941.93   205.5 1941.04   216.3 1942.43
   237.5 1946.31   273.5  1946.2   301.5 1947.53   313.5 1947.22   341.5 1943.91
   361.5 1948.72   381.5 1948.54   397.5 1946.08   453.5 1942.25   457.5 1943.17
   473.5  1952.5   489.5 1954.17   505.5  1963.1   521.5 1970.22     553 1981.13
#Mann= 4 ,-1,0
       0      .1       0  156.49    .045       0   216.3      .1       0
     480     .08       0
#XS Ineff= 2 , 0
                          376.24            1955
Permanent Ineff=
       F       F
Bank Sta=156.49,216.3
XS Rating Curve= 0 ,0
Exp/Cntr(USF)=0,0
Exp/Cntr=0.3,0.1

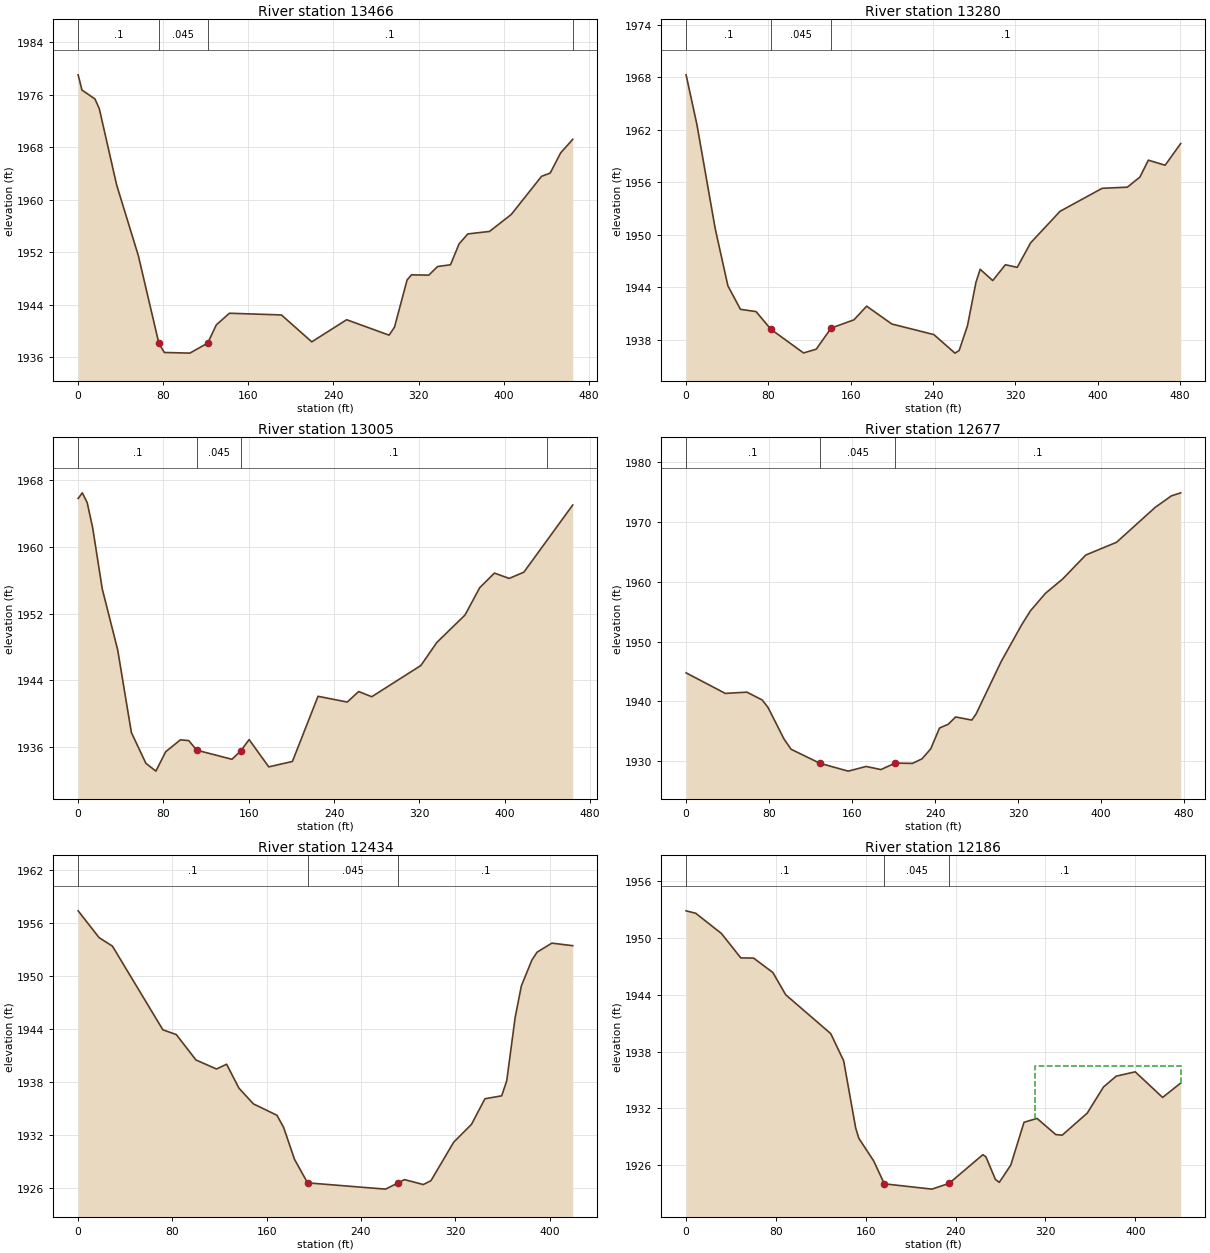
Type RM Length L Ch R = 1 ,13466   ,184.3,186.2,185.4
XS GIS Cut Line= 2
2199399.64768797646161.6460302292199488.59143947646617.966146623
#Sta/Elev= 30
       0 1979.04     3.6 1976.72    15.8 1975.36    19.9 1973.87    36.2 1962.25
    56.6 1951.47   75.871938.125      81 1936.72     105 1936.62   121.8 1938.15
   129.9 1940.93   142.2  1942.7   191.1 1942.44   219.6 1938.34   252.4 1941.71
   292.3 1939.36   297.4 1940.59   309.2 1947.77   313.3 1948.55   329.6 1948.51
   337.9 1949.82     350 1950.09   358.1 1953.28   366.3 1954.79   386.7 1955.17
   407.1 1957.75   435.6 1963.57   443.7 1964.06   453.6 1967.15   464.9  1969.2
#Mann= 4 ,-1,0
       0      .1       0   75.87    .045       0   121.8      .1       0
  464.91     .08       0
Bank Sta=75.87,121.8
XS Rating Curve= 0 ,0
Exp/Cntr(USF)=0,0
Exp/Cntr=0.3,0.1

Type RM Length L Ch R = 1 ,13280   ,279.8,275.1,261.4
XS GIS Cut Line= 2
2199219.53677967646201.4554759242199317.20008723646671.919581166
#Sta/Elev= 30
       0 1968.28    10.5  1962.6    28.3 1950.68    40.6 1944.15    52.8 1941.46
      68  1941.2    82.31939.185   114.1 1936.47   126.4  1936.9   140.91939.312
   163.1 1940.26   175.4 1941.82   199.9 1939.78   240.7 1938.57   261.2 1936.45
   265.3 1936.75   273.4  1939.6   281.6 1944.55   285.7 1946.04   297.9 1944.75
   310.2 1946.56   321.7 1946.26   334.7 1949.06   363.3 1952.67   404.2  1955.3
   428.7 1955.43   440.9 1956.59   449.1 1958.52   465.4 1957.94   480.5 1960.42
#Mann= 3 ,-1,0
       0      .1       0    82.3    .045       0   140.9      .1       0
Bank Sta=82.3,140.9
XS Rating Curve= 0 ,0
Exp/Cntr(USF)=0,0
Exp/Cntr=0.3,0.1

Type RM Length L Ch R = 1 ,13005   ,323.6,327.7,316.4
XS GIS Cut Line= 2
2198957.00100666646333.7735055232199185.93220072646737.028452873
#Sta/Elev= 30
       0 1965.81     3.9 1966.49     8.5 1965.31    13.6 1962.31    22.6 1954.98
    37.1 1947.65    49.9 1937.76    63.5 1934.07    72.9 1933.13    82.1 1935.46
    95.9 1936.88   103.7 1936.79   111.2 1935.64   144.2 1934.55   152.3 1935.53
   160.3 1936.91   178.7 1933.64   200.9 1934.29   224.9  1942.1   252.3 1941.41
     263 1942.67   275.3 1942.05   321.3 1945.79   336.4 1948.57   362.7 1951.84
   376.5 1955.12   390.3 1956.87   404.1 1956.23   417.9 1956.98   463.7 1965.03
#Mann= 4 ,-1,0
       0      .1       0   111.2    .045       0   152.3      .1       0
     440     .08       0
Bank Sta=111.2,152.3
XS Rating Curve= 0 ,0
Exp/Cntr(USF)=0,0
Exp/Cntr=0.3,0.1

Type RM Length L Ch R = 1 ,12677   ,237.5,242.8,244.9
XS GIS Cut Line= 2
2198671.36208562646516.4984035412199003.20730271646858.845051552
#Sta/Elev= 30
       0 1944.77    37.8 1941.34    58.6 1941.55    73.4 1940.24    78.9 1939.02
    94.4 1933.73   101.2 1932.02   129.1 1929.67   156.3 1928.37   173.6 1929.15
   187.8 1928.63   201.5 1929.71   218.2 1929.66   227.4 1930.42   235.8 1932.08
   244.3 1935.56   252.8  1936.2   259.8 1937.41   275.4 1936.89   279.5 1937.89
   303.7 1946.64   323.5 1952.79     332 1955.13   346.3 1958.02   363.2 1960.46
   385.3 1964.43     415 1966.56   452.2 1972.38   467.8  1974.3   476.8 1974.81
#Mann= 3 ,-1,0
       0      .1       0   129.1    .045       0   201.5      .1       0
Bank Sta=129.1,201.5
XS Rating Curve= 0 ,0
Exp/Cntr(USF)=0,0
Exp/Cntr=0.3,0.1

Type RM Length L Ch R = 1 ,12434   ,253.3,248.7,244.9
XS GIS Cut Line= 2
2198458.00405796646606.3647877322198719.03463301 646935.06995632
#Sta/Elev= 30
       0 1957.41    17.8 1954.37    29.1 1953.41    71.9 1943.93    83.3 1943.39
     100 1940.51   117.4 1939.49     126 1940.03   136.4 1937.33   148.7 1935.54
   168.7 1934.25   174.4 1932.86   183.6 1929.26   194.71926.591   260.8 1925.88
  271.471926.578   276.9 1926.96   292.9  1926.4   299.4 1926.84   318.7  1931.2
   333.8 1933.22   345.2 1936.12   359.4 1936.45   363.7 1938.15   370.8 1945.29
   376.1  1948.9     385 1951.82   389.4 1952.72     402 1953.75   419.7 1953.46
#Mann= 3 ,-1,0
       0      .1       0   194.7    .045       0  271.47      .1       0
Bank Sta=194.7,271.47
XS Rating Curve= 0 ,0
Exp/Cntr(USF)=0,0
Exp/Cntr=0.3,0.1

Type RM Length L Ch R = 1 ,12186   ,346,339.7,335.1
XS GIS Cut Line= 2
2198272.61700144646811.1764026592198587.65992906647118.868328634
#Sta/Elev= 30
       0 1952.89     8.6 1952.63    31.5 1950.49    48.7 1947.91    60.1 1947.89
    77.3 1946.36    88.7 1944.01   128.8  1939.9   140.3 1937.03     151 1929.92
   153.8 1928.83   167.1 1926.42   176.5 1924.01   218.9 1923.45   234.2 1924.06
   264.2 1927.09     267 1926.86   275.5 1924.46   278.9 1924.17   289.1 1925.99
   300.9 1930.52   312.5 1930.93   329.2 1929.22   334.9 1929.16   357.2 1931.49
   371.7 1934.26     383  1935.4   399.9 1935.86   424.3 1933.15   440.4 1934.67
#Mann= 3 ,-1,0
       0      .1       0   176.5    .045       0   234.2      .1       0
#XS Ineff= 2 , 0
                          310.99         1936.47
Permanent Ineff=
       F       F
Bank Sta=176.5,234.2
XS Rating Curve= 0 ,0
Exp/Cntr(USF)=0,0
Exp/Cntr=0.3,0.1