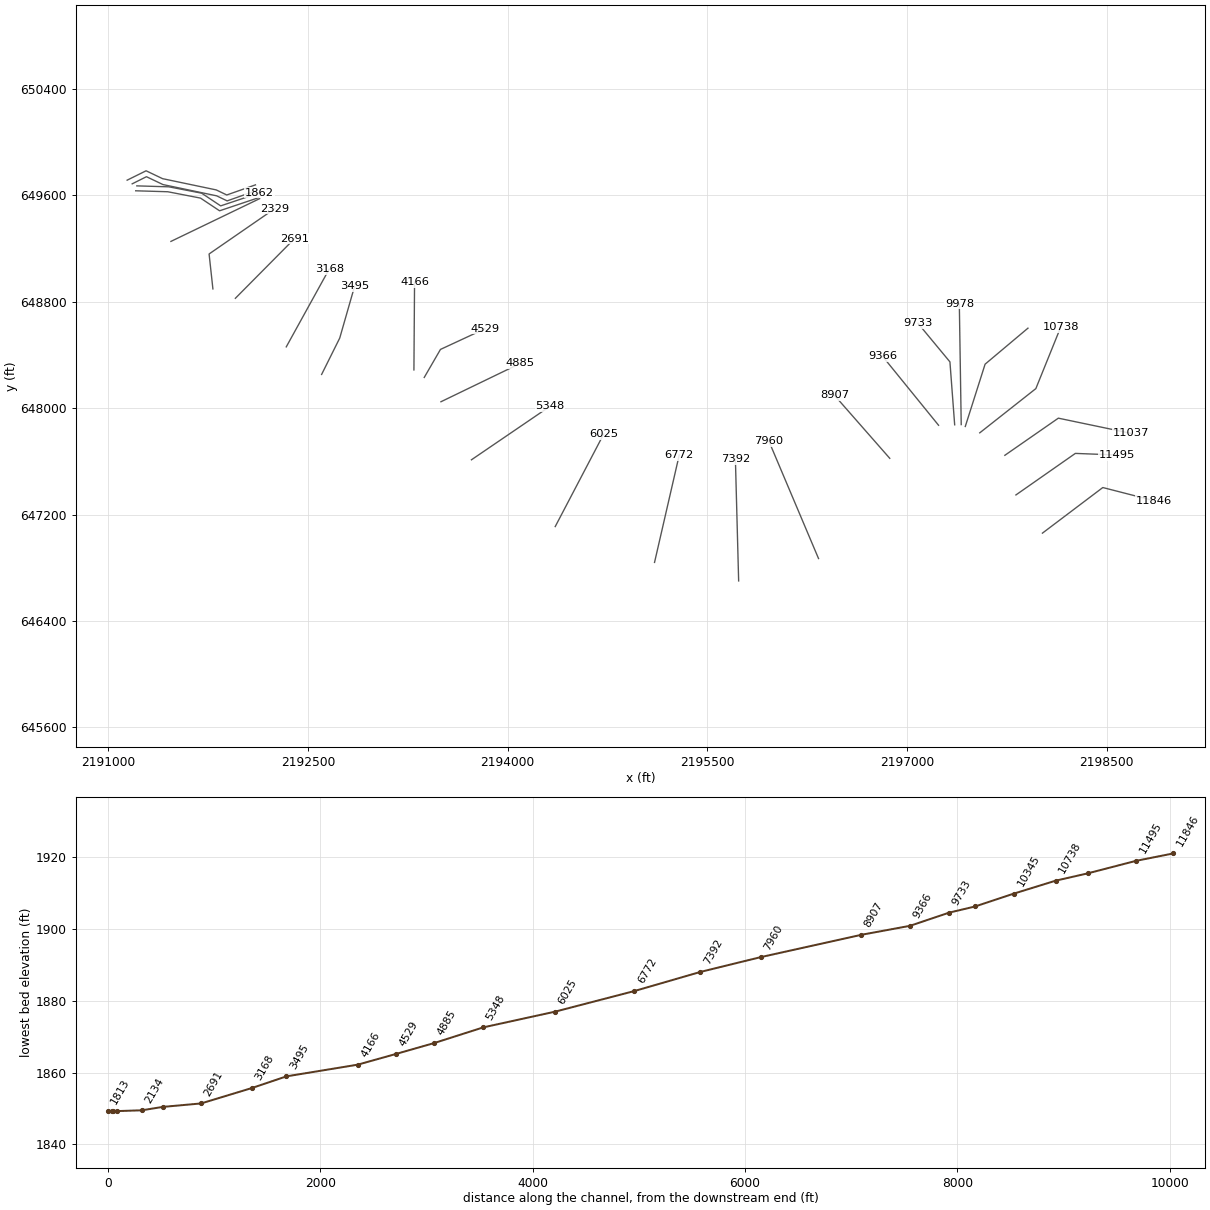
HEC-RAS study LFBUCKRV.prj: LFBUCKRV

--- LFBUCKRV.g01 (geometry) --- (continued)

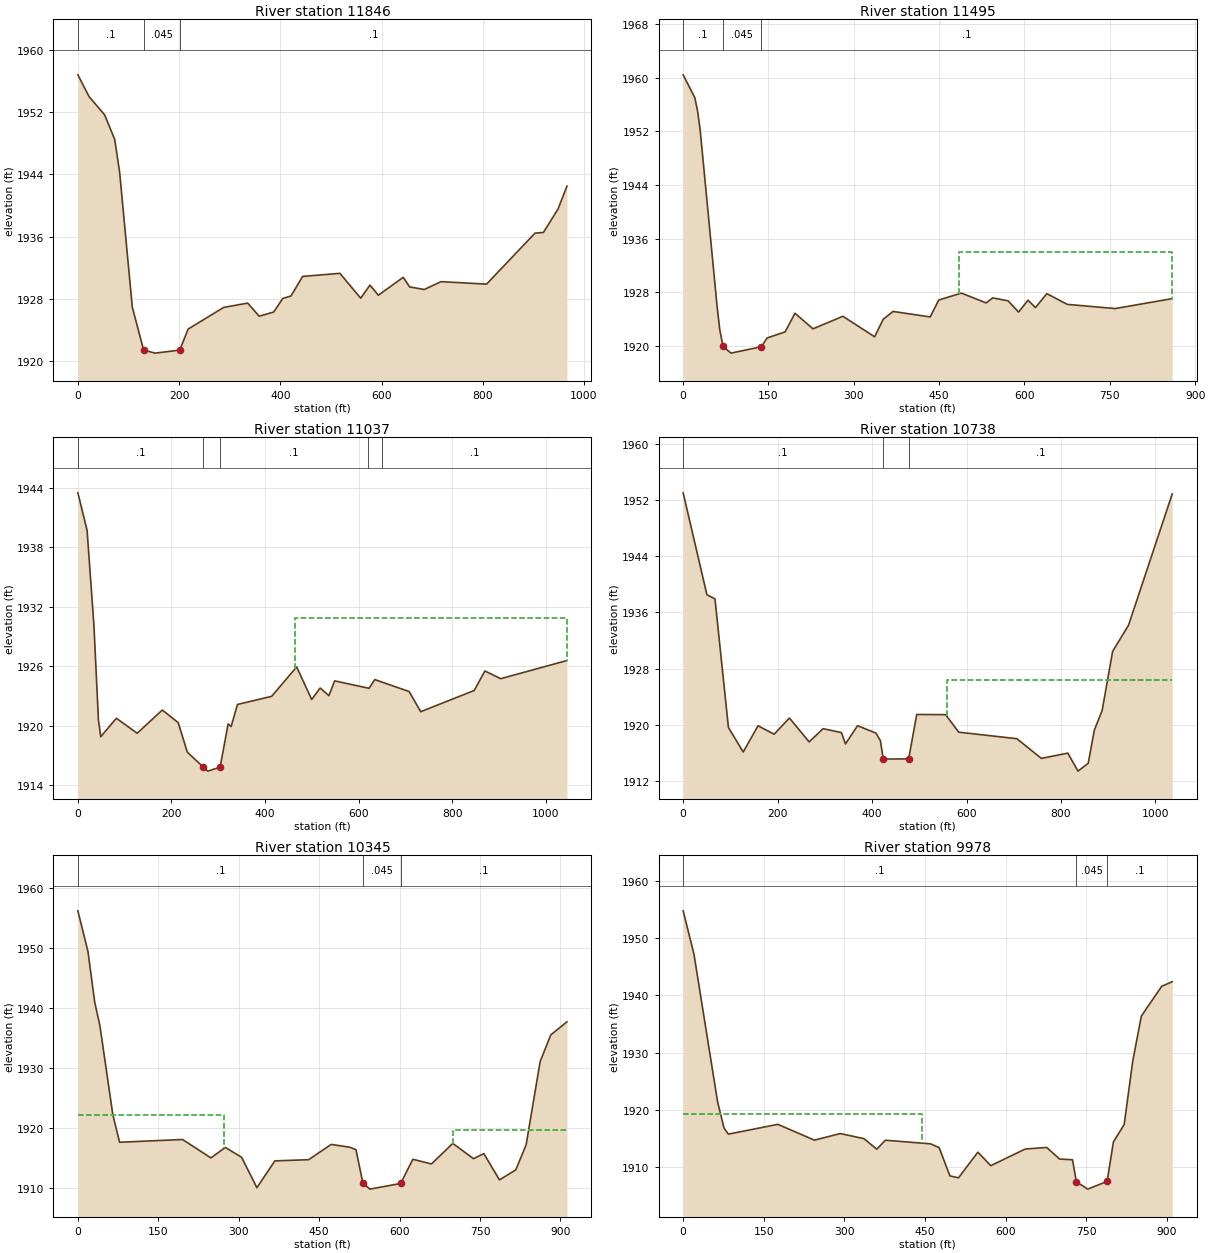
Type RM Length L Ch R = 1 ,11846   ,349.8,350.9,347.9
XS GIS Cut Line= 3
2198018.39313189647061.0213092892198471.96943128647403.882134025
2198857.14955143647304.880324699
#Sta/Elev= 30
       0 1956.82    22.3    1954    52.8 1951.68    72.8 1948.51    82.5  1944.3
   107.5 1926.93   129.9 1921.39   152.7    1921   201.3 1921.39   217.8 1924.09
     288 1926.88   335.5 1927.44   358.3 1925.75   386.9 1926.29   404.9 1928.04
   421.2 1928.36     444 1930.87   517.7 1931.27   558.8 1928.07   577.1 1929.75
   593.6 1928.45   642.9 1930.76   655.5 1929.52   684.4 1929.19   717.5  1930.2
   807.5 1929.88   903.3 1936.45   919.8 1936.53   948.8 1939.56   966.3 1942.49
#Mann= 3 ,-1,0
       0      .1       0   129.9    .045       0   201.3      .1       0
Bank Sta=129.9,201.3
XS Rating Curve= 0 ,0
Exp/Cntr(USF)=0,0
Exp/Cntr=0.3,0.1

Type RM Length L Ch R = 1 ,11495   ,466.5,458,434.8
XS GIS Cut Line= 3
2197819.35007464647348.2563502942198265.78636847647660.517801714
2198580.48736248647648.320088768
#Sta/Elev= 30
       0  1960.4    20.5    1957    25.4 1954.99      30 1952.11    59.6 1925.95
    64.4  1922.4    70.2 1919.93      84 1918.94   137.7 1919.89   147.4 1921.19
   179.3 1922.11   196.6 1924.88   228.2 1922.56   280.8 1924.43   336.6 1921.37
   351.7 1923.99   368.9 1925.15   434.3 1924.33   449.3 1926.85   489.1 1927.88
   532.6 1926.42   544.1 1927.17   571.2 1926.73   589.6 1925.06   606.3 1926.83
   619.2 1925.72   639.3  1927.8   675.3  1926.2   759.4 1925.58   859.7 1927.06
#Mann= 3 ,-1,0
       0      .1       0    70.2    .045       0   137.7      .1       0
#XS Ineff= 2 , 0
                          485.63         1933.97
Permanent Ineff=
       F       F
Bank Sta=70.2,137.7
XS Rating Curve= 0 ,0
Exp/Cntr(USF)=0,0
Exp/Cntr=0.3,0.1

Type RM Length L Ch R = 1 ,11037   ,292.6,299.7,302.7
XS GIS Cut Line= 3
2197736.03481613647646.2220821412198137.95921588647925.435050105
2198682.15773943647811.615751063
#Sta/Elev= 30
       0 1943.49    19.7 1939.71    34.3 1930.15      44 1920.58    48.9  1918.9
    82.3 1920.76   126.8 1919.25   180.5 1921.59   214.5 1920.32     234 1917.34
     268 1915.84   277.8 1915.43     304 1915.83   321.2 1920.19   327.7 1919.93
   341.1 1922.15   414.2 1922.97   467.7 1925.94   499.8 1922.65   517.8 1923.81
   536.6 1923.04   548.9 1924.53   622.4 1923.78   634.7 1924.66   708.2 1923.45
   732.8 1921.42   847.2 1923.56     870 1925.53   903.8 1924.75  1045.4 1926.58
#Mann= 5 ,-1,0
       0      .1       0     268    .045       0     304      .1       0
  619.39     .07       0  649.39      .1       0
#XS Ineff= 2 , 0
                           463.1         1930.82
Permanent Ineff=
       F       F
Bank Sta=268,304
XS Rating Curve= 0 ,0
Exp/Cntr(USF)=0,0
Exp/Cntr=0.3,0.1

Type RM Length L Ch R = 1 ,10738   ,389.2,392.8,389.3
XS GIS Cut Line= 3
2197547.52160209647815.1726041582197969.00869386648147.738368548
2198155.74348135648610.129270909
#Sta/Elev= 30
       0 1952.99    50.3  1938.5    67.4  1937.9    95.9 1919.61   127.2 1916.13
   158.5 1919.86   192.7 1918.66     225 1920.96   266.8 1917.57   296.4 1919.45
   335.1 1918.89   343.7 1917.28   369.3 1919.87   408.4 1918.81   417.7 1917.73
   423.7 1915.13   477.5 1915.15   494.6 1921.47   555.8 1921.44   583.5 1918.95
   706.7 1918.02   758.5 1915.22   814.5 1915.97   836.1 1913.41   857.7 1914.52
   870.6 1919.22   887.2 1922.04   909.4 1930.44     943 1934.15  1035.6 1952.84
#Mann= 3 ,-1,0
       0      .1       0   423.7    .045       0   477.5      .1       0
#XS Ineff= 2 , 0
                          558.42         1926.43
Permanent Ineff=
       F       F
Bank Sta=423.7,477.5
XS Rating Curve= 0 ,0
Exp/Cntr(USF)=0,0
Exp/Cntr=0.3,0.1

Type RM Length L Ch R = 1 ,10345   ,344.4,366.8,393.5
XS GIS Cut Line= 3
2197438.78143072 647862.999836622197587.59352866 648331.39201375
2197909.61315044648602.181241153
#Sta/Elev= 30
       0 1956.25    18.8 1949.49    31.5 1940.97    41.1 1937.09    65.2 1922.25
    77.8 1917.64   195.3  1918.1   248.1 1915.03   275.1 1916.78   305.4 1915.13
   333.9 1910.06   367.4 1914.53   430.4 1914.73   472.4 1917.28   506.7 1916.82
   518.7 1916.41   531.5 1910.85   544.5 1909.82     602 1910.76   624.8  1914.8
   659.5 1914.02   699.3 1917.45   737.9  1914.9   757.2 1915.75   786.3 1911.36
   816.8 1913.03   836.1 1917.23   862.2 1931.09   882.1 1935.56   912.2 1937.73
#Mann= 3 ,-1,0
       0      .1       0   531.5    .045       0     602      .1       0
#XS Ineff= 2 , 0
          272.68 1922.21  700.12         1919.61
Permanent Ineff=
       F       F
Bank Sta=531.5,602
XS Rating Curve= 0 ,0
Exp/Cntr(USF)=0,0
Exp/Cntr=0.3,0.1

Type RM Length L Ch R = 1 ,9978    ,227.1,244.5,265.4
XS GIS Cut Line= 2
2197408.25104729 647877.127927672197393.92838199648786.617174092
#Sta/Elev= 30
       0 1954.76    20.1 1947.21    64.1 1921.42    76.1 1916.85    84.1 1915.81
   176.1 1917.52   244.1 1914.76   292.1 1915.91   336.1 1915.03   360.1 1913.19
   376.1 1914.75   460.1 1914.12   476.1 1913.46   496.1 1908.53   512.1 1908.19
   548.1 1912.67   572.1 1910.31   636.1 1913.21   676.1 1913.49   700.1 1911.47
   724.1 1911.34  731.341907.515   752.4 1906.22   788.5 1907.57   800.2 1914.45
   820.2 1917.48   836.2 1928.57   852.2 1936.41   890.1  1941.6   909.6  1942.4
#Mann= 3 ,-1,0
       0      .1       0  731.34    .045       0   788.5      .1       0
#XS Ineff= 2 , 0
          443.38 1919.26
Permanent Ineff=
       F       F
Bank Sta=731.34,788.5
XS Rating Curve= 0 ,0
Exp/Cntr(USF)=0,0
Exp/Cntr=0.3,0.1

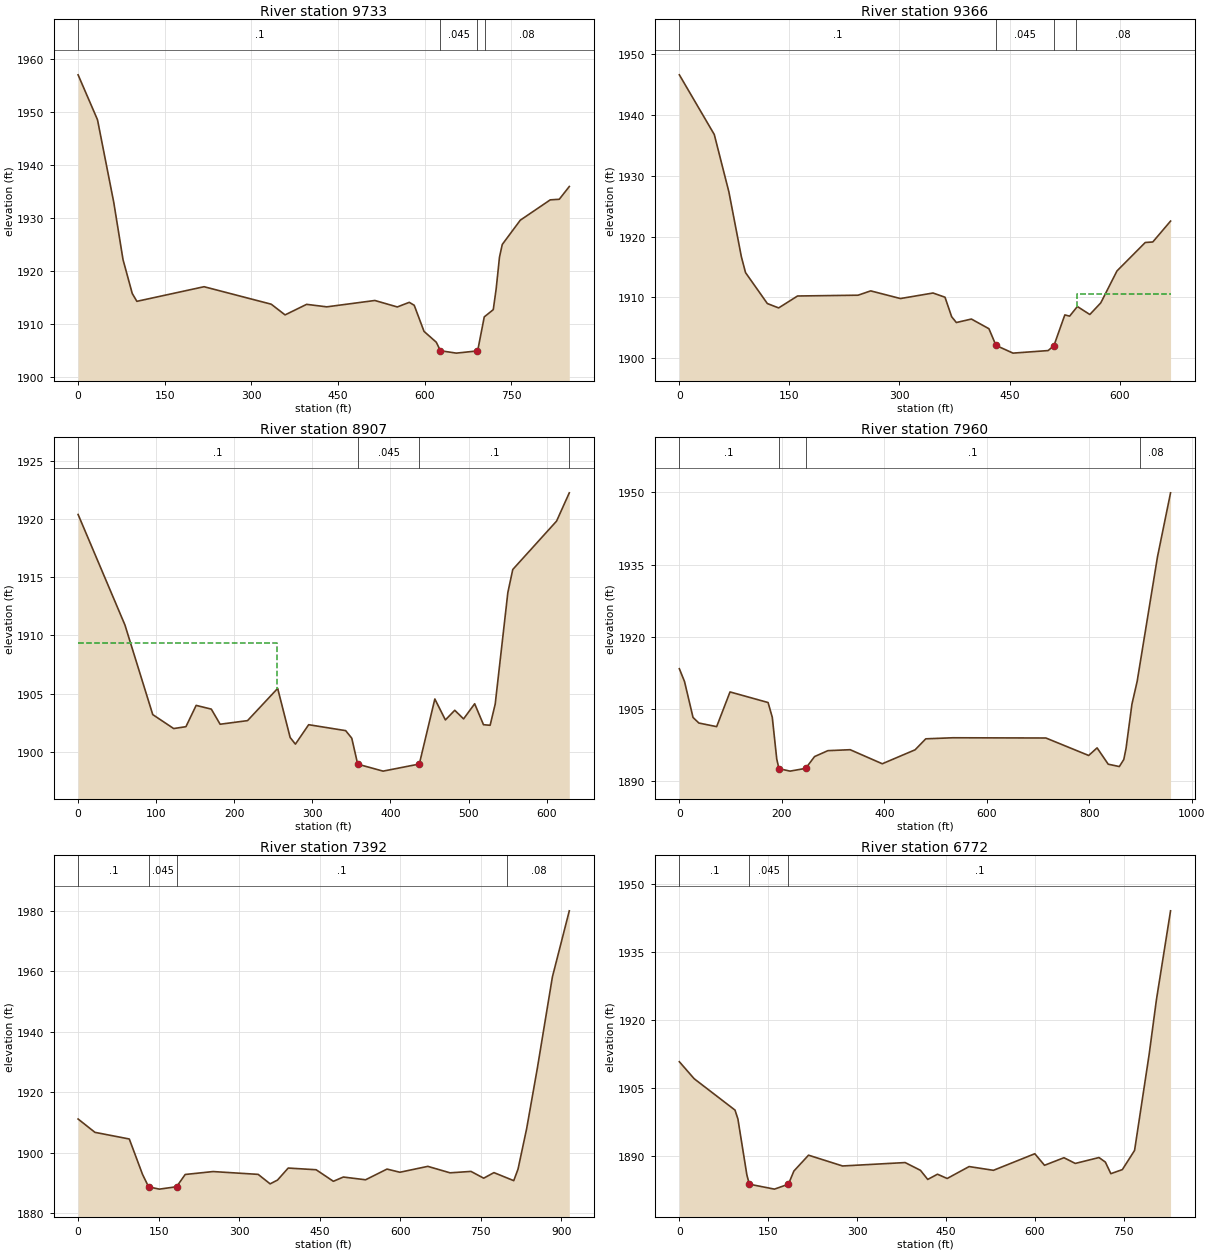
Type RM Length L Ch R = 1 ,9733    ,367.1,367.6,365.3
XS GIS Cut Line= 3
2197359.00838805647875.639106774 2197323.4398571 648348.70056842
2197083.35227319648638.584095669
#Sta/Elev= 30
       0 1957.05    33.6 1948.57    61.7 1933.01    77.8 1922.16    93.8 1915.76
   101.8 1914.28   218.2 1917.04   334.5 1913.74   358.5 1911.72   395.8 1913.71
   430.8 1913.24     514 1914.44   552.9 1913.22   573.6 1914.09   582.2 1913.53
   599.2  1908.6   620.4 1906.56   627.6 1904.95   655.1  1904.5   690.1  1904.9
     693 1905.45   703.5 1911.34   719.1 1912.71   724.1 1916.61   729.9 1922.64
   734.7 1925.02   765.9  1929.6   817.8 1933.44   833.4 1933.55   850.8 1935.96
#Mann= 4 ,-1,0
       0      .1       0   627.6    .045       0   690.1      .1       0
   704.4     .08       0
Bank Sta=627.6,690.1
XS Rating Curve= 0 ,0
Exp/Cntr(USF)=0,0
Exp/Cntr=0.3,0.1

Type RM Length L Ch R = 1 ,9366    ,457.2,459,460.1
XS GIS Cut Line= 2
2197237.97047097647872.0884713612196816.24754831 648391.94817477
#Sta/Elev= 30
       0 1946.58    47.6 1936.77    67.5 1927.34    84.5 1916.69    90.2 1914.07
   119.9 1908.99   135.3 1908.27   161.1 1910.23   243.5 1910.36   260.8 1911.07
   301.3 1909.81   345.7 1910.72     362 1910.03   371.1 1906.82   377.5 1905.87
     398 1906.44   421.9 1904.85   431.5 1902.11   454.7 1900.84   502.6 1901.26
  510.461902.074   525.3 1907.12   531.9 1906.92   542.4  1908.5   559.4 1907.19
   574.3  1909.1   596.4 1914.35   634.9 1919.02   645.2 1919.11   669.4 1922.54
#Mann= 4 ,-1,0
       0      .1       0   431.5    .045       0  510.46      .1       0
     540     .08       0
#XS Ineff= 2 , 0
                          542.25         1910.64
Permanent Ineff=
       F       F
Bank Sta=431.5,510.46
XS Rating Curve= 0 ,0
Exp/Cntr(USF)=0,0
Exp/Cntr=0.3,0.1

Type RM Length L Ch R = 1 ,8907    ,950,946.8,947.8
XS GIS Cut Line= 2
2196871.23732713647623.5284131482196456.46726058648096.511822369
#Sta/Elev= 30
       0 1920.39      60 1910.89    95.6 1903.19   122.4 1901.99   138.1 1902.15
   151.2 1903.98   170.6 1903.66   181.9 1902.36     217 1902.67   255.6 1905.44
   271.6 1901.22   278.3 1900.65   295.3 1902.32   342.7 1901.81   350.5 1901.16
  358.09 1898.93   390.6 1898.33     437 1898.94   456.9 1904.53   470.4 1902.73
   482.4 1903.56   493.7 1902.82   507.9 1904.12   519.2 1902.32   527.7 1902.27
   534.2 1904.09   550.4 1913.68   556.7 1915.66   612.8 1919.82   629.1 1922.25
#Mann= 4 ,-1,0
       0      .1       0  358.09    .045       0     437      .1       0
  629.08     .08       0
#XS Ineff= 2 , 0
          254.76 1909.31
Permanent Ineff=
       F       F
Bank Sta=358.09,437
XS Rating Curve= 0 ,0
Exp/Cntr(USF)=0,0
Exp/Cntr=0.3,0.1

Type RM Length L Ch R = 1 ,7960    ,573.1,567.7,553.5
XS GIS Cut Line= 2
2196336.10818039646870.1060028072195962.85816424647753.220420105
#Sta/Elev= 30
       0 1913.39    10.1 1910.73    26.7 1903.27    38.1 1902.11    72.8 1901.36
    98.9 1908.57   173.2 1906.37   181.4  1903.3   190.1 1894.64   194.4 1892.64
     216 1892.12   246.5 1892.69   263.9 1895.14   289.9 1896.37   333.4 1896.57
   396.1 1893.65   460.2 1896.55     481 1898.83   534.1 1899.05   715.5    1899
     799 1895.37   815.4 1896.95   837.1 1893.56   858.8 1893.07   867.5 1894.53
   871.9 1896.84   883.4 1906.02   893.6 1910.76   933.3 1936.64   958.8 1949.93
#Mann= 4 ,-1,0
       0      .1       0   194.4    .045       0   246.5      .1       0
     900     .08       0
Bank Sta=194.4,246.5
XS Rating Curve= 0 ,0
Exp/Cntr(USF)=0,0
Exp/Cntr=0.3,0.1

Type RM Length L Ch R = 1 ,7392    ,622.8,620.5,610.1
XS GIS Cut Line= 2
2195735.98070345646701.7775641512195711.58527755647616.606035108
#Sta/Elev= 30
       0 1911.19    31.4 1906.78    95.4 1904.58     120 1892.89   131.4 1888.74
   151.5    1888   183.5 1888.79   199.5 1892.84   251.5 1893.81   335.5 1892.88
   357.8 1889.74   371.5 1890.99   391.5 1894.97   443.5 1894.41   475.6 1890.59
   494.2    1892   535.6 1891.09   575.6 1894.63   599.6 1893.58   651.6 1895.53
     693 1893.39     732 1893.86   755.7 1891.62   774.8 1893.46   811.7  1890.8
   819.7 1894.64   835.7 1907.97   855.7 1928.03   883.7 1958.18   915.2 1980.04
#Mann= 4 ,-1,0
       0      .1       0   131.4    .045       0   183.5      .1       0
     800     .08       0
Bank Sta=131.4,183.5
XS Rating Curve= 0 ,0
Exp/Cntr(USF)=0,0
Exp/Cntr=0.3,0.1

Type RM Length L Ch R = 1 ,6772    ,758.3,746.5,741.6
XS GIS Cut Line= 2
 2195103.9772658646840.8509192592195289.64144559647648.342748816
#Sta/Elev= 30
       0  1910.8      25 1907.05    93.9 1900.13    98.8 1898.15   113.9 1885.82
  118.031883.782   160.4 1882.69     184 1883.78   193.2 1886.68   217.9 1890.18
   275.3  1887.8   380.9 1888.55   406.7 1886.84     419 1884.83   435.4 1885.98
   451.8 1885.04   488.8 1887.67   529.8 1886.84   599.6  1890.5     616 1887.95
   648.8 1889.62   667.9 1888.36   707.9 1889.66   718.6 1888.66   727.9  1886.1
   747.3    1887   767.9 1891.23   792.5 1912.43   804.8 1924.51   828.6  1944.1
#Mann= 3 ,-1,0
       0      .1       0  118.03    .045       0     184      .1       0
Bank Sta=118.03,184
XS Rating Curve= 0 ,0
Exp/Cntr(USF)=0,0
Exp/Cntr=0.3,0.1

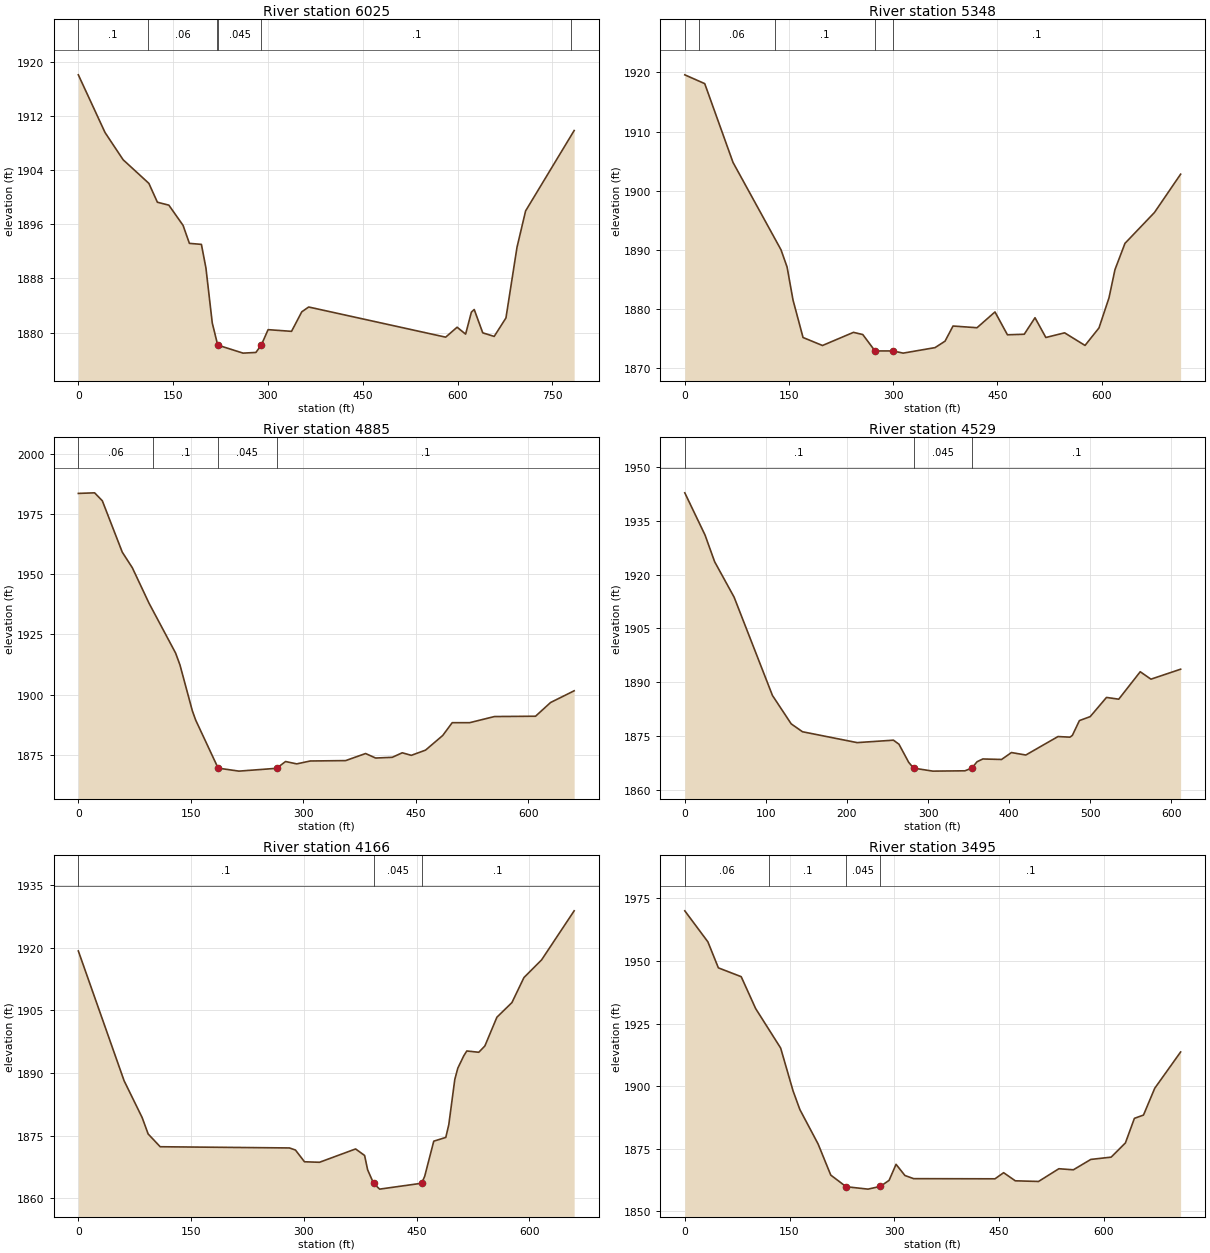
Type RM Length L Ch R = 1 ,6025    ,690.6,677.5,668.2
XS GIS Cut Line= 2
2194357.88114825647110.3409150572194721.71453995647805.262693221
#Sta/Elev= 30
       0  1918.1    42.3 1909.56    70.9 1905.54   111.6 1902.05   125.1 1899.26
   143.2 1898.83   165.7 1895.84   175.7 1893.18   194.7 1893.03   201.9 1889.52
   211.9  1881.4   220.5 1878.14   260.6 1876.95   280.9 1877.05   289.5 1878.15
   300.2 1880.42   337.3 1880.17   353.5 1883.06   364.4 1883.77   581.1 1879.31
   599.2 1880.78   612.7 1879.76   621.8 1883.01   626.3  1883.4   639.8 1879.95
   657.9 1879.42   676.5 1882.15     694 1892.61   707.6 1897.98   784.4 1909.86
#Mann= 6 ,-1,0
       0      .1       0     110     .06       0     220      .1       0
   220.5    .045       0   289.5      .1       0     780     .08       0
Bank Sta=220.5,289.5
XS Rating Curve= 0 ,0
Exp/Cntr(USF)=0,0
Exp/Cntr=0.3,0.1

Type RM Length L Ch R = 1 ,5348    ,467.1,462.8,454.3
XS GIS Cut Line= 2
2193728.44938059647612.4309956152194318.17193528648014.450120733
#Sta/Elev= 30
       0 1919.59    28.7  1918.1    69.4 1904.79   138.5 1890.02   147.2 1887.12
   155.8 1881.52   170.2  1875.2   198.2 1873.85   242.8 1876.07   256.2  1875.7
   273.8 1872.93   299.7 1872.93   314.3 1872.56   360.2 1873.49   374.6 1874.58
   386.1 1877.14   420.6 1876.85   446.5 1879.52   464.4 1875.66   488.6 1875.75
   504.1 1878.54   519.7  1875.2   546.7 1875.99   576.1 1873.86   596.2 1876.82
   610.6  1881.9   619.2 1886.67   633.6 1891.11     676 1896.32   713.7  1902.8
#Mann= 5 ,-1,0
       0      .1       0      20     .06       0     130      .1       0
   273.8    .045       0   299.7      .1       0
Bank Sta=273.8,299.7
XS Rating Curve= 0 ,0
Exp/Cntr(USF)=0,0
Exp/Cntr=0.3,0.1

Type RM Length L Ch R = 1 ,4885    ,355.7,355.9,354.3
XS GIS Cut Line= 2
2193499.38013186648048.9911895262194094.48687499648336.876762015
#Sta/Elev= 30
       0 1983.54    21.7 1983.78      32 1980.47    58.6 1959.13      72 1952.66
    94.2 1937.97   129.7 1917.22   135.5 1912.31     152 1893.27   156.4 1889.43
   186.4 1869.43   214.2 1868.19   264.3 1869.36   276.3 1872.18   291.2  1871.2
   309.2  1872.4   356.4 1872.56     383  1875.5   396.4 1873.63   418.6 1873.93
   431.9 1875.81     444 1874.75     463 1876.92   485.9 1883.01   498.5 1888.31
   521.8 1888.31   554.8 1890.86   609.6 1890.99   629.6 1896.67   661.1 1901.56
#Mann= 4 ,-1,0
       0     .06       0     100      .1       0   186.4    .045       0
   264.3      .1       0
Bank Sta=186.4,264.3
XS Rating Curve= 0 ,0
Exp/Cntr(USF)=0,0
Exp/Cntr=0.3,0.1

Type RM Length L Ch R = 1 ,4529    ,327.6,363.5,401.4
XS GIS Cut Line= 3
2193373.74900971 648231.580364622193495.67062269648442.344083196
2193829.30108304648597.345203584
#Sta/Elev= 30
       0 1942.79      25    1931    36.8 1923.58    60.8  1913.7   108.1 1886.28
   131.2 1878.37   145.1 1876.17   212.5 1873.14   257.3 1873.82   264.1 1872.69
   276.1 1867.64   282.1 1866.03   305.8 1865.19   345.5 1865.28     354 1866.05
   360.4 1867.81   367.5 1868.58   390.6 1868.44   402.8 1870.37   420.5 1869.68
   460.2 1874.83   474.9 1874.66   477.9 1875.15   486.6 1879.28   499.9 1880.39
     520 1885.74   535.1 1885.25   561.6  1892.9   574.8 1890.83   611.4 1893.61
#Mann= 3 ,-1,0
       0      .1       0   282.1    .045       0     354      .1       0
Bank Sta=282.1,354
XS Rating Curve= 0 ,0
Exp/Cntr(USF)=0,0
Exp/Cntr=0.3,0.1

Type RM Length L Ch R = 1 ,4166    ,668.2,670.3,650.2
XS GIS Cut Line= 2
2193296.24844951648288.2880915912193300.97409343648947.987982022
#Sta/Elev= 30
       0 1919.21    60.9 1888.13    84.9 1879.32    92.9 1875.39   108.9 1872.33
   280.9 1872.04   288.9 1871.54   300.9 1868.73   320.9 1868.61   368.9  1871.8
   380.9 1870.24   384.9 1866.81   392.9 1863.54   400.9 1862.18   456.9 1863.59
   460.9 1865.29   472.9 1873.66   488.9 1874.56   492.9 1877.61   500.9 1888.46
   504.9 1891.14   512.9 1894.13   516.9 1895.26   532.8 1894.95   540.9 1896.46
   556.9 1903.34   576.9 1906.85   592.9 1912.84   616.4 1917.08   659.7 1928.82
#Mann= 3 ,-1,0
       0      .1       0   392.9    .045       0   456.9      .1       0
Bank Sta=392.9,456.9
XS Rating Curve= 0 ,0
Exp/Cntr(USF)=0,0
Exp/Cntr=0.3,0.1

Type RM Length L Ch R = 1 ,3495    ,324.1,327.7,324
XS GIS Cut Line= 3
2192602.75003027648254.2829344492192738.87969035648527.838727567
2192850.37636432648916.780613516
#Sta/Elev= 30
       0 1970.03    33.1 1957.64    48.1 1947.26    80.8 1943.74   101.5    1931
   137.3 1915.25   155.1 1898.12   164.8 1890.71   190.9 1876.98   209.1 1864.53
   231.1 1859.89   262.4 1858.93   280.2 1860.03   292.6 1862.43   302.6 1868.83
   315.3 1864.37   327.8 1863.11   444.3 1863.05   456.7 1865.49   473.4 1862.25
   506.7 1861.99   535.8 1867.07   556.6 1866.65   581.6 1870.79   610.7  1871.7
   631.1 1877.36     644 1887.19     657 1888.49   673.1 1899.19   710.2 1913.68
#Mann= 4 ,-1,0
       0     .06       0     120      .1       0   231.1    .045       0
   280.2      .1       0
Bank Sta=231.1,280.2
XS Rating Curve= 0 ,0
Exp/Cntr(USF)=0,0
Exp/Cntr=0.3,0.1

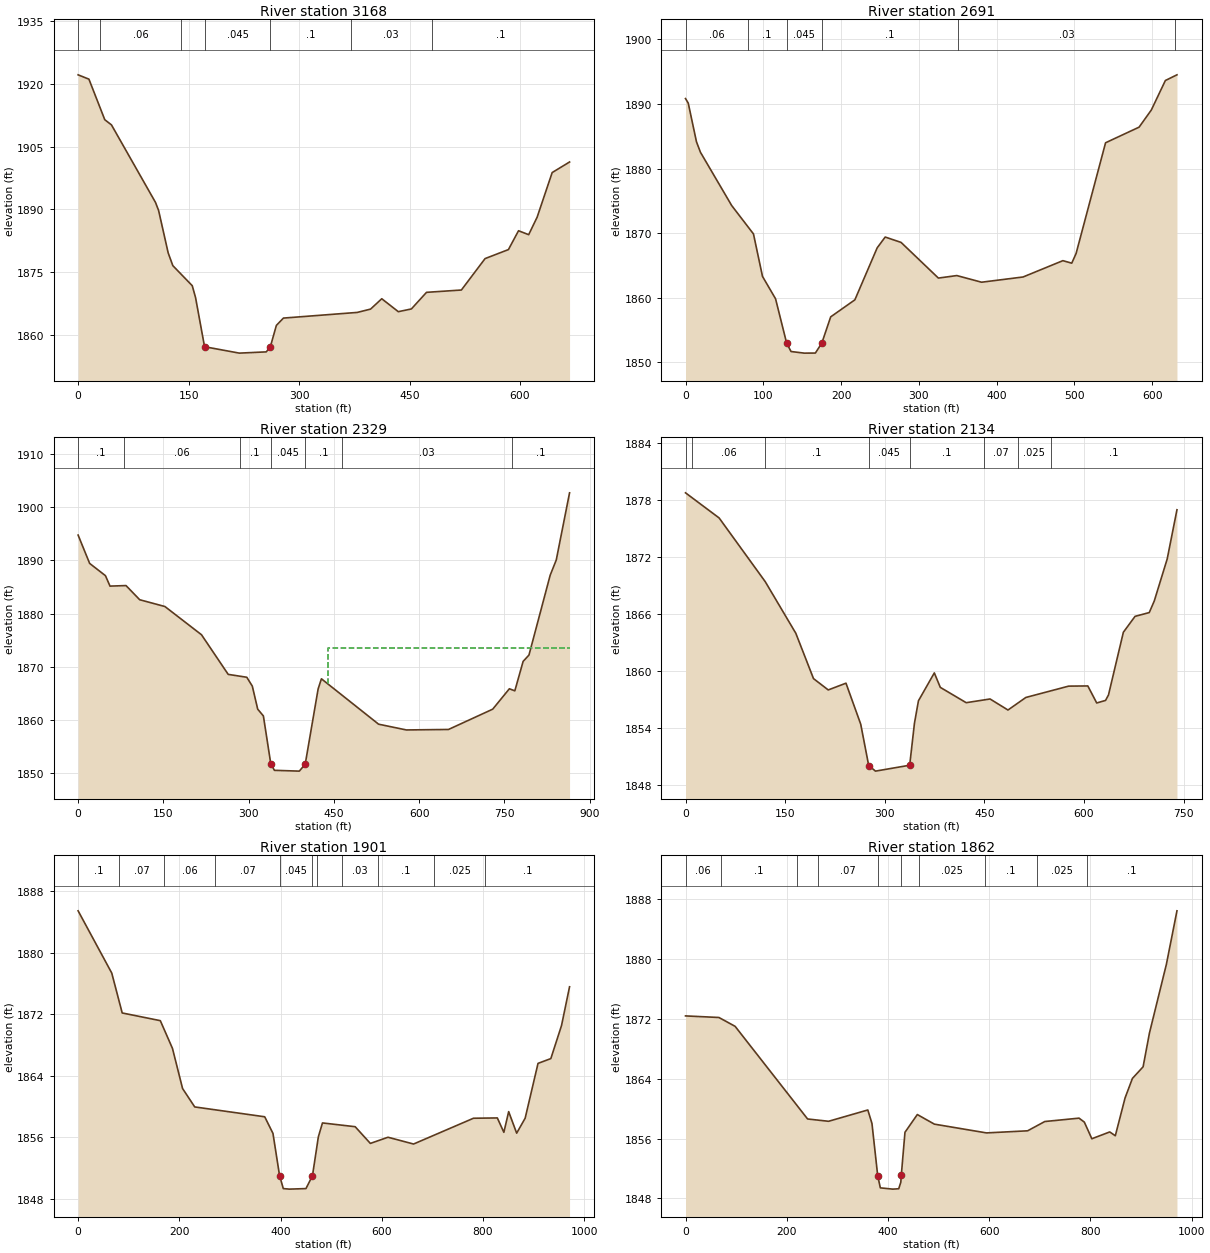
Type RM Length L Ch R = 1 ,3168    ,488.1,476.2,469.8
XS GIS Cut Line= 2
2192337.09584292648461.4839501082192659.35581213649045.848694266
#Sta/Elev= 30
       0 1922.13    14.7 1921.09    36.2 1911.41    45.3 1910.17   105.1 1891.65
   109.3 1889.73   122.3  1879.6   128.6 1876.56     155 1871.76   159.5 1868.91
  171.69 1857.19   218.9 1855.66   255.5 1855.96   261.1 1857.23   269.2 1862.28
   278.8 1864.03   378.9 1865.38   397.1 1866.17   412.3 1868.65   434.8 1865.56
   452.5 1866.21   473.1 1870.18   520.4 1870.73   552.6 1878.24   584.3 1880.39
     598 1884.89   611.8 1883.95   623.3 1888.14   643.7 1898.79   667.3 1901.31
#Mann= 7 ,-1,0
       0      .1       0      30     .06       0     140      .1       0
  171.69    .045       0   261.1      .1       0     370     .03       0
     480      .1       0
Bank Sta=171.69,261.1
XS Rating Curve= 0 ,0
Exp/Cntr(USF)=0,0
Exp/Cntr=0.3,0.1

Type RM Length L Ch R = 1 ,2691    ,365.7,362,356.4
XS GIS Cut Line= 2
2191954.68067947648826.7119152072192399.39943697649275.727472299
#Sta/Elev= 30
       0 1890.84     3.5 1890.14    14.1 1884.14    19.2 1882.52    59.4 1874.26
    87.4 1869.86      99 1863.28   115.8 1859.81   130.1 1852.92   135.7 1851.64
   152.7 1851.39     167  1851.4   175.3 1852.95   186.7 1857.01   217.8 1859.65
   246.5 1867.71   256.8 1869.38   277.2 1868.55   325.2 1863.02   348.9 1863.41
   380.7 1862.38   434.1 1863.19   485.3 1865.72   496.7 1865.33   502.3 1866.84
   540.2 1883.99   583.3 1886.41     599 1889.06   617.1 1893.64     632 1894.52
#Mann= 6 ,-1,0
       0     .06       0      80      .1       0   130.1    .045       0
   175.3      .1       0     350     .03       0     630      .1       0
Bank Sta=130.1,175.3
XS Rating Curve= 0 ,0
Exp/Cntr(USF)=0,0
Exp/Cntr=0.3,0.1

Type RM Length L Ch R = 1 ,2329    ,198.9,195.7,189.4
XS GIS Cut Line= 3
2191785.95031987648897.3871147142191757.30498927649159.969311844
2192251.43694205649501.326168113
#Sta/Elev= 30
       0 1894.73    20.3 1889.41    48.1 1887.11    56.1 1885.15    84.3 1885.25
   108.4 1882.59   152.7 1881.32   217.1 1876.02   264.1 1868.58   296.8 1868.04
   306.5 1866.38     316 1862.05     326 1860.78     339 1851.81   345.4 1850.57
   389.2 1850.42  399.581851.712   422.3 1865.84   428.1 1867.75   528.7 1859.23
   577.6 1858.15   651.7 1858.24   729.5 1862.05   758.8 1865.88   768.4 1865.49
     783 1871.02   793.3 1872.21   830.6 1887.19   841.3 1890.05   864.7 1902.66
#Mann= 7 ,-1,0
       0      .1       0      80     .06       0  284.14      .1       0
     339    .045       0  399.58      .1       0  464.14     .03       0
  764.14      .1       0
#XS Ineff= 2 , 0
                          438.94         1873.62
Permanent Ineff=
       F       F
Bank Sta=339,399.58
XS Rating Curve= 0 ,0
Exp/Cntr(USF)=0,0
Exp/Cntr=0.3,0.1

Type RM Length L Ch R = 1 ,2134    ,254.2,232.5,215.2
XS GIS Cut Line= 2
2191470.61630211649254.5158821732192137.00340004649576.041174556
#Sta/Elev= 30
       0 1878.72    50.6 1876.08     120 1869.39   166.1 1863.96   192.7  1859.2
   214.9 1858.01   241.6 1858.72   263.8 1854.41   275.8 1850.07     286 1849.48
   337.5  1850.1   344.7 1854.52   350.7 1856.87   374.6  1859.8   383.6 1858.28
   422.6 1856.67   458.5 1857.06   485.5  1855.9   512.4 1857.22   576.8 1858.41
   605.7 1858.43   619.1 1856.64   632.4 1856.91   636.8 1857.48   659.2 1864.07
   676.8 1865.74   698.2 1866.14   705.7 1867.35   725.2 1871.77   739.9 1876.94
#Mann= 8 ,-1,0
       0      .1       0      10     .06       0     120      .1       0
   275.8    .045       0   337.5      .1       0     450     .07       0
     500    .025       0     550      .1       0
Bank Sta=275.8,337.5
XS Rating Curve= 0 ,0
Exp/Cntr(USF)=0,0
Exp/Cntr=0.3,0.1

Type RM Length L Ch R = 1 ,1901    ,41.6,39.6,52.5
XS GIS Cut Line= 5
 2191205.8823753649635.0043775612191446.98057448649627.843044912
2191692.85299543649580.1008272522191836.07964841649484.616391932
2192127.30717614649582.487938135
#Sta/Elev= 30
       0 1885.42    66.5 1877.33    87.1 1872.15   162.4 1871.15   186.4 1867.55
   206.4 1862.33   230.4 1859.94   368.7 1858.66     385  1856.5     398 1851.03
   405.4 1849.33   417.6 1849.26   450.2 1849.33  463.051851.006   474.7 1856.06
   482.8 1857.86   547.4 1857.37   577.4  1855.2   612.3    1856   662.8 1855.12
   781.2 1858.47   828.3 1858.51   841.2 1856.64   850.7 1859.33   866.5 1856.53
   883.3 1858.48   908.7  1865.6     934 1866.22   955.1 1870.51     971 1875.55
#Mann= 11 ,-1,0
       0      .1       0      80     .07       0     170     .06       0
   271.2     .07       0     398    .045       0  463.05     .07       0
   471.2    .025       0  521.67     .03       0  591.67      .1       0
  703.81    .025       0  803.81      .1       0
Bank Sta=398,463.05
XS Rating Curve= 0 ,0
Exp/Cntr(USF)=0,0
Exp/Cntr=0.3,0.1

Type RM Length L Ch R = 1 ,1862    ,7.5,4.9,5.1
XS GIS Cut Line= 5
2191214.24826797649672.0045962482191455.34646715649664.843263599
 2191701.2188881649617.1010459392191844.44554108649521.616610619
2192135.67306881649619.488156822
#Sta/Elev= 30
       0 1872.36      66 1872.15      98 1870.97   241.2 1858.61   282.6  1858.3
   360.2 1859.81   368.4 1858.01   379.71851.065   384.9 1849.42   409.5 1849.25
   421.3  1849.3   425.4 1850.17  426.361851.117   433.6 1856.83     458  1859.2
   491.7 1857.92   594.7 1856.75   675.9 1857.03   709.9 1858.27   777.5 1858.72
     788 1858.19   802.8 1855.97   838.2 1856.88   849.2 1856.37   868.5 1861.42
     883 1864.02   904.1 1865.57   916.7 1870.09   950.1 1879.24     971 1886.38
#Mann= 10 ,-1,0
       0     .06       0      70      .1       0     220     .06       0
   261.2     .07       0   379.7    .045       0  426.36     .07       0
   461.2    .025       0  591.67      .1       0  693.81    .025       0
  793.81      .1       0
Bank Sta=379.7,426.36
XS Rating Curve= 0 ,0
Exp/Cntr(USF)=0,0
Exp/Cntr=0.3,0.1

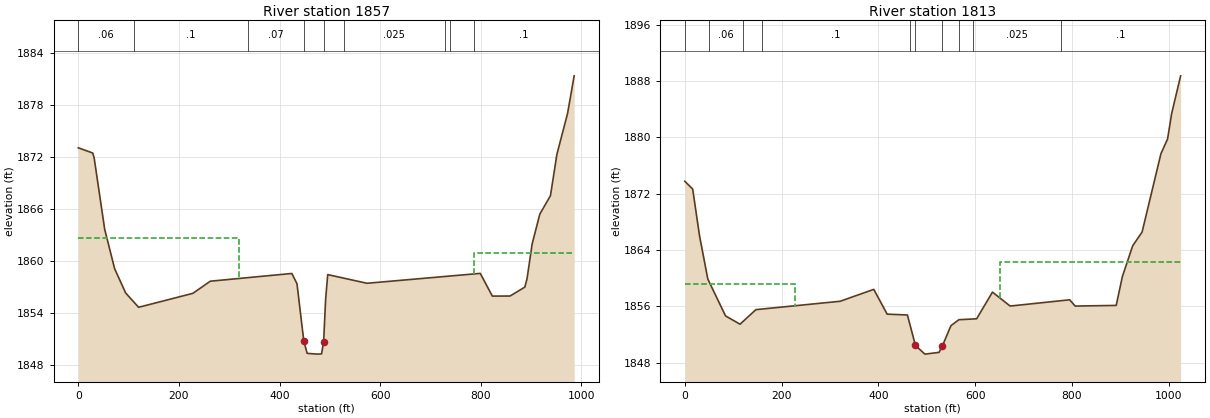
Type RM Length L Ch R = 1 ,1857    ,48.4,43.9,43.3
XS GIS Cut Line= 6
2191179.61723296649687.4293190272191286.74418097649740.992793028
2191410.78591023649681.7910586062191813.92153035649597.217152288
2191892.85717625649559.1588944442192108.52063736649635.275410131
#Sta/Elev= 30
       0 1873.04    28.6 1872.44    31.5 1871.86    52.4 1863.64    72.2 1859.09
    94.1  1856.3   119.8 1854.65   227.7 1856.26   262.3 1857.66   424.4 1858.55
   434.6 1857.37   448.1 1850.78   454.8 1849.34   475.1 1849.25   483.4 1849.28
   487.5 1850.64   491.6 1855.63   495.7 1858.42   573.7 1857.42   798.9 1858.56
   822.9 1855.94   858.1 1855.95   887.5 1856.98   891.8 1857.93     902 1861.95
   917.2 1865.39   938.4 1867.52   951.2 1872.29   972.4    1877   985.5 1881.34
#Mann= 9 ,-1,0
       0     .06       0     110      .1       0  337.22     .07       0
   448.1    .045       0   487.5     .07       0  527.22    .025       0
  729.13      .1       0  739.13    .025       0  786.76      .1       0
#XS Ineff= 2 , 0
          320.13 1862.66  786.58         1860.96
Permanent Ineff=
       F       F
Bank Sta=448.1,487.5
XS Rating Curve= 0 ,0
Exp/Cntr(USF)=0,0
Exp/Cntr=0.3,0.1

Type RM Length L Ch R = 1 ,1813    ,226.1,255.1,260.3
XS GIS Cut Line= 6
2191141.55897512 649714.915838582191283.92505076649785.394093846
2191407.96678002649726.1923594232191811.10240014649641.618453105
2191890.03804604649603.5601952612192105.70150715649679.676710948
#Sta/Elev= 30
       0 1873.78    16.3 1872.67    30.5 1866.01    47.6 1859.88    84.2 1854.65
   114.1 1853.47   146.9 1855.54     321 1856.73   390.5 1858.42   418.1  1854.9
     460 1854.78   476.6 1850.45   496.1 1849.22   525.4 1849.47  532.381850.411
   549.9 1853.26   566.3 1854.11     603 1854.24   635.7 1858.03   672.3 1856.05
   795.3 1856.94   806.6 1856.05   891.4 1856.14   904.2 1860.25   925.4  1864.6
   944.9 1866.57   983.8 1877.69   997.5 1879.78    1006 1883.41  1024.5 1888.76
#Mann= 10 ,-1,0
       0      .1       0      50     .06       0     120     .07       0
  158.86      .1       0   466.3     .07       0   476.6    .045       0
  532.38     .07       0   566.3      .1       0   596.3    .025       0
  778.21      .1       0
#XS Ineff= 2 , 0
          228.38 1859.15  652.15         1862.34
Permanent Ineff=
       F       F
Bank Sta=476.6,532.38
XS Rating Curve= 0 ,0
Exp/Cntr(USF)=0,0
Exp/Cntr=0.3,0.1