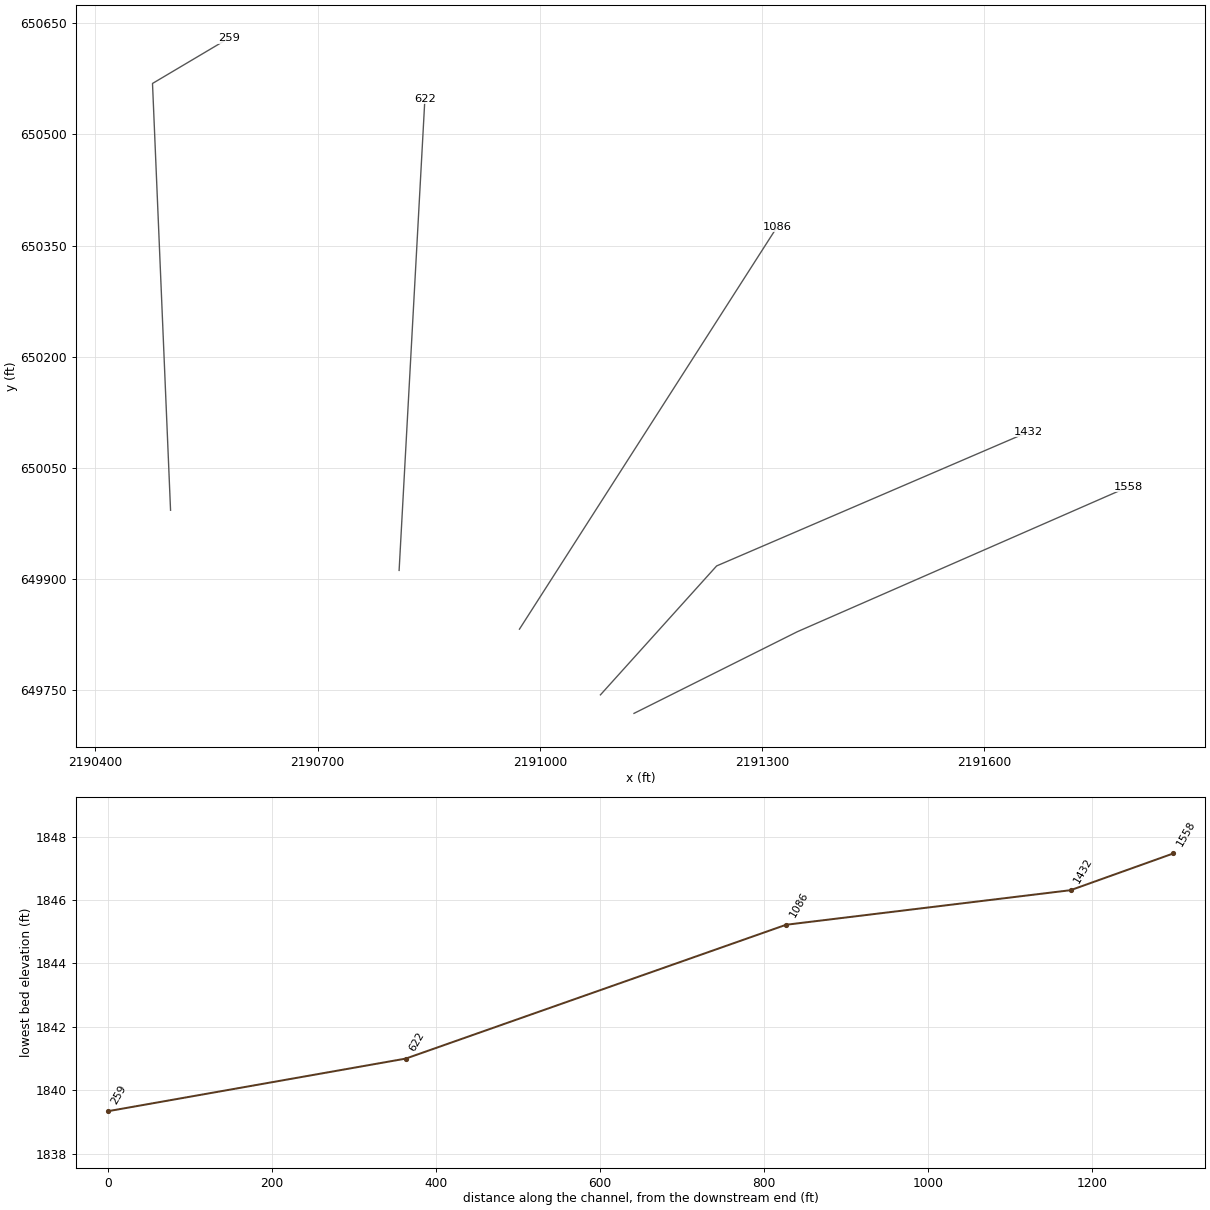
HEC-RAS study LFBUCKRV.prj: LFBUCKRV

--- LFBUCKRV.g01 (geometry) --- (continued)

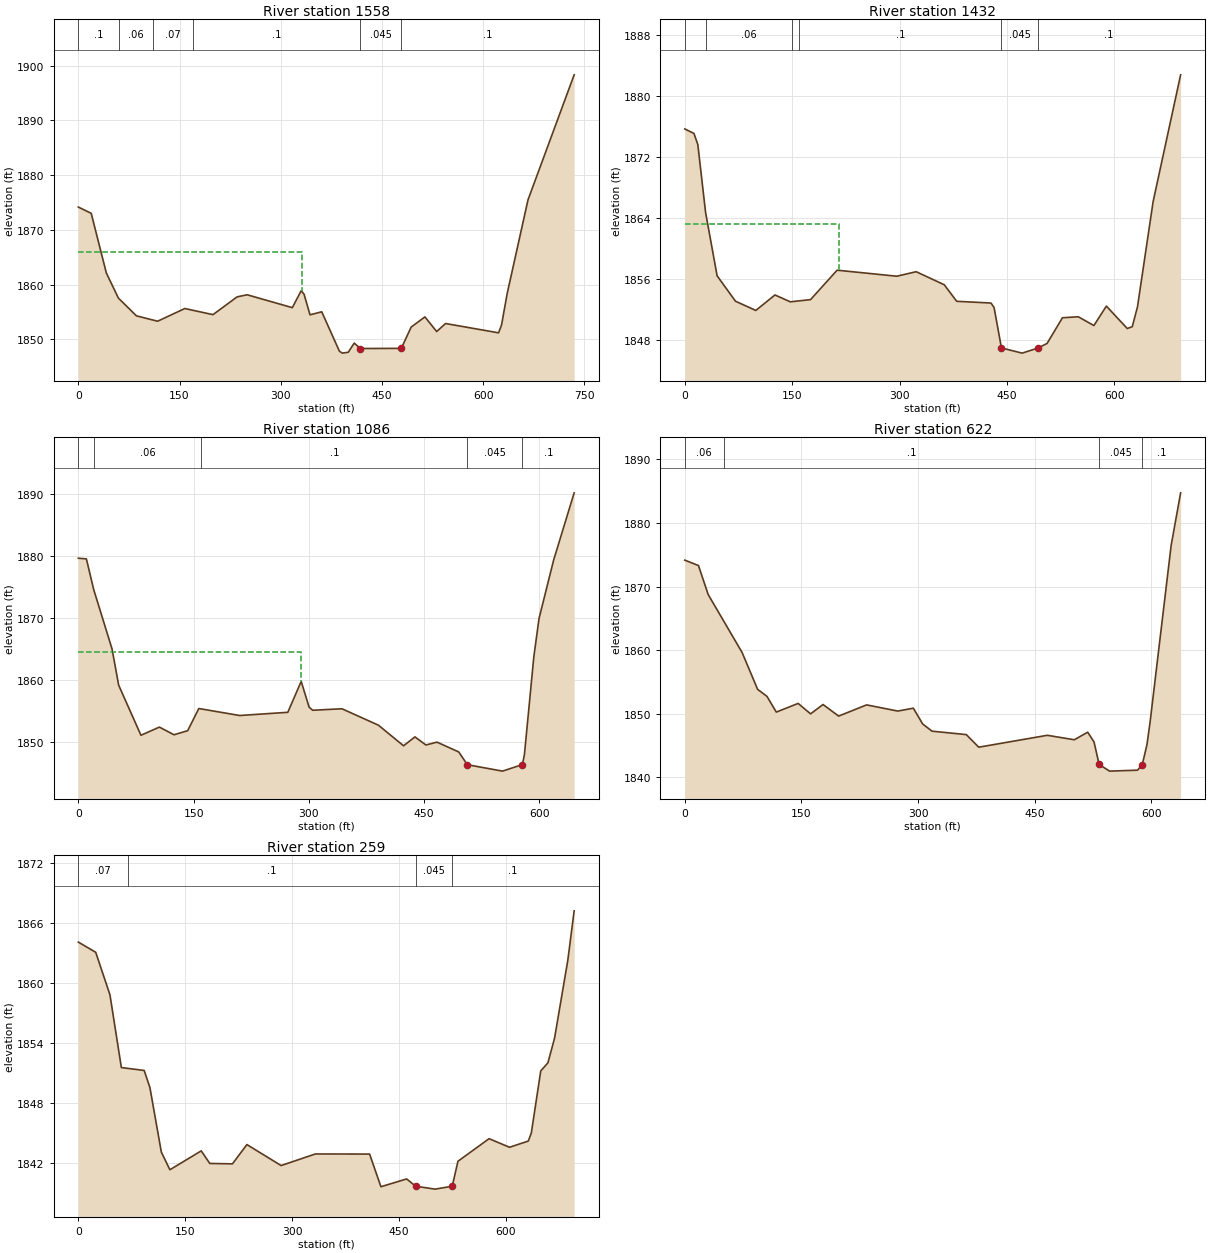
Type RM Length L Ch R = 1 ,1558    ,126.9,125.4,129.1
XS GIS Cut Line= 3
2191127.05096953649718.6531994032191347.45137157649828.853400422
 2191794.7345404650024.620816348
#Sta/Elev= 30
       0 1874.16    19.1 1873.01    41.5 1862.12    59.4 1857.52    86.1 1854.28
   117.5  1853.3   157.8 1855.62   199.5  1854.5   235.3 1857.75   250.2 1858.13
   317.1 1855.78   330.2 1858.87   334.5 1858.23   343.3 1854.47   360.7 1855.02
   386.9 1847.81   391.3 1847.47     400 1847.63   408.8  1849.3     418 1848.31
   478.6 1848.34   493.2 1852.23   513.6 1854.09     531 1851.41   544.1 1852.88
   622.7 1851.18   627.1 1852.61   635.4 1858.32   666.3 1875.47   734.7 1898.32
#Mann= 6 ,-1,0
       0      .1       0      60     .06       0     110     .07       0
     170      .1       0     418    .045       0   478.6      .1       0
#XS Ineff= 2 , 0
          330.82 1865.94
Permanent Ineff=
       F       F
Bank Sta=418,478.6
XS Rating Curve= 0 ,0
Exp/Cntr(USF)=0,0
Exp/Cntr=0.3,0.1

Type RM Length L Ch R = 1 ,1432    ,328.8,346.7,367.5
XS GIS Cut Line= 3
2191081.74788994649743.6403978292191238.58107496649917.660781199
 2191659.4631219650098.603093869
#Sta/Elev= 30
       0 1875.72    12.8 1875.13    18.2 1873.67      29 1864.79    45.1 1856.46
    70.8 1853.12    99.2 1851.91   125.9 1853.94   147.3 1853.04   175.6 1853.33
   212.7 1857.19     296  1856.4   323.1 1856.99   362.3 1855.28   379.7 1853.11
   427.6 1852.88   431.9 1852.29   442.2 1846.99   471.1 1846.31   492.9 1846.97
   505.9 1847.58   527.4 1850.95   549.5 1851.08   571.3 1849.93   588.7 1852.48
   617.9 1849.54   624.9 1849.78   632.2  1852.4     654 1866.19   692.4 1882.82
#Mann= 6 ,-1,0
       0      .1       0      30     .06       0     150     .07       0
     160      .1       0   442.2    .045       0   492.9      .1       0
#XS Ineff= 2 , 0
          214.85  1863.3
Permanent Ineff=
       F       F
Bank Sta=442.2,492.9
XS Rating Curve= 0 ,0
Exp/Cntr(USF)=0,0
Exp/Cntr=0.3,0.1

Type RM Length L Ch R = 1 ,1086    ,452.3,463.5,483.2
XS GIS Cut Line= 2
2190972.45191751649832.3325717132191320.49268425650375.662879793
#Sta/Elev= 30
       0  1879.6    10.5 1879.49      20 1874.54    43.8 1864.98    52.5  1859.1
    81.5 1851.01   105.5 1852.33   124.5 1851.09   142.3 1851.75   156.8 1855.33
     210  1854.2   272.6 1854.72     290 1859.71   300.3 1855.55     305 1855.05
     343 1855.29   390.5 1852.64   423.2 1849.31     438 1850.75   452.3 1849.44
   466.7  1849.9     495 1848.32  506.191846.259     552 1845.22   577.9 1846.28
   580.5  1847.9   592.7 1863.66   599.5 1869.87   618.5  1879.3   645.2 1890.16
#Mann= 5 ,-1,0
       0      .1       0      20     .06       0     160      .1       0
  506.19    .045       0   577.9      .1       0
#XS Ineff= 2 , 0
          290.25 1864.43
Permanent Ineff=
       F       F
Bank Sta=506.19,577.9
XS Rating Curve= 0 ,0
Exp/Cntr(USF)=0,0
Exp/Cntr=0.3,0.1

Type RM Length L Ch R = 1 ,622     ,361.1,363.2,364.4
XS GIS Cut Line= 2
2190810.03289303649911.608524138 2190844.8369697650548.414654569
#Sta/Elev= 30
       0 1874.16    17.6 1873.31    30.1 1868.75    73.7 1859.65    93.7 1853.85
   105.7 1852.75   117.7 1850.28   145.8 1851.64   161.8    1850   177.8 1851.47
   197.9 1849.65   233.9 1851.41     274 1850.44     294 1850.89     306 1848.41
     318 1847.28   362.1 1846.74   378.1 1844.76   466.3 1846.63   501.1 1845.93
   518.3 1847.12   526.4 1845.59  532.991842.046   546.4    1841   582.4 1841.15
   588.5 1842.04   594.5 1845.16   598.5 1848.68   625.6 1876.46   637.8 1884.74
#Mann= 4 ,-1,0
       0     .06       0      50      .1       0  532.99    .045       0
   588.5      .1       0
Bank Sta=532.99,588.5
XS Rating Curve= 0 ,0
Exp/Cntr(USF)=0,0
Exp/Cntr=0.3,0.1

Type RM Length L Ch R = 1 ,259     ,,,
XS GIS Cut Line= 3
2190501.54521922649992.8180363772190477.18236555650568.825505335
2190579.85439174650629.732639515
#Sta/Elev= 30
       0 1864.07    24.4 1863.05    44.4 1858.79    60.4 1851.51    92.4 1851.22
   100.5  1849.5   116.5 1843.05   128.5 1841.28   172.5 1843.17   184.5 1841.91
   216.3 1841.87   236.6  1843.8   284.6  1841.7   332.7 1842.86   408.8 1842.85
   424.7 1839.58   460.8 1840.36  473.611839.627   500.8 1839.34   524.8 1839.63
   532.8 1842.13   576.5 1844.39   605.2 1843.53   631.5 1844.15   635.8 1844.96
     649 1851.17   659.1 1851.99   668.4 1854.45     687 1862.25   695.9  1867.2
#Mann= 4 ,-1,0
       0     .07       0      70      .1       0  473.61    .045       0
   524.8      .1       0
Bank Sta=473.61,524.8
XS Rating Curve= 0 ,0
Exp/Cntr(USF)=0,0
Exp/Cntr=0.3,0.1
LCMann Table=0

Chan Stop Cuts=-1
Use User Specified Reach Order=0
Composite Channel Slope=5